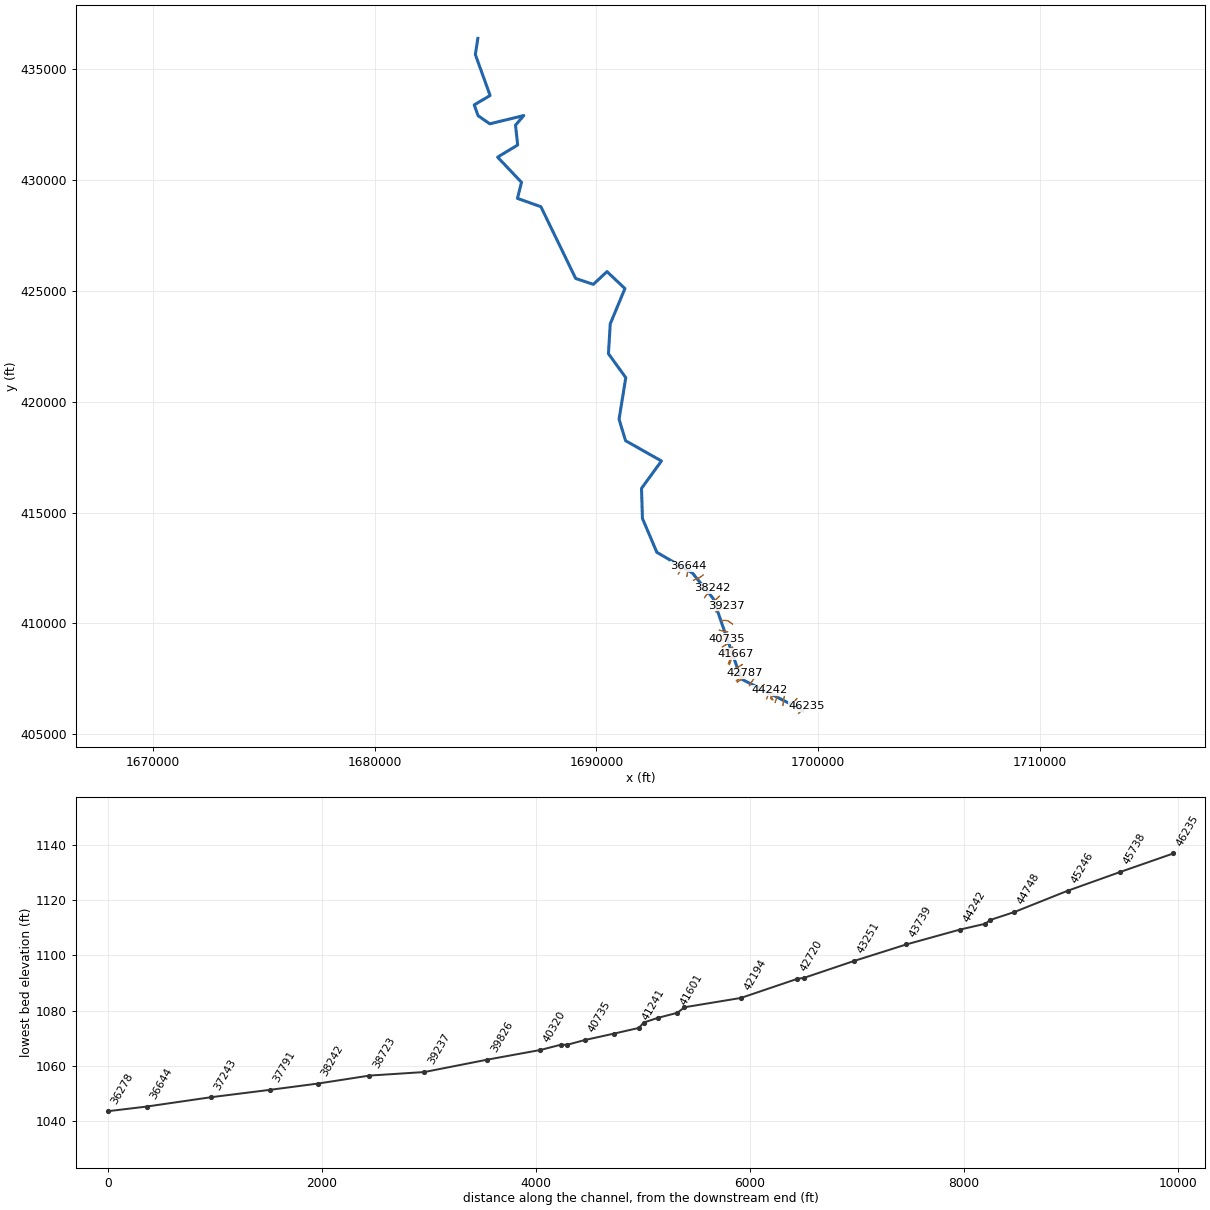
--- LNGDRN.prj (project) ---

Proj Title=LNGDRN
Current Plan=p01
Default Exp/Contr=0,0
English Units
Geom File=g01
Flow File=f01
Plan File=p01
BEGIN DESCRIPTION:
---------- MODELED AS PART OF WVEMD CTP PROGRAM, 2023----------
Stream Name: Long Drain
Flood Zone:  AFH
Wetzel County, WV
HEC-RAS Version: RAS 6.3
Vertical Datum: NAVD88
Projection: NAD 1983 StatePlane West Virginia S FIPS 4702 (US Feet)
Terrain: 1-meter West Virginia FEMA R3 South Central (collected 2018-2020)
Land Use: 2019 NLCD
Hydrologic Method:
WV SIR2010-5033 regression equations
Additional Model Notes:
Coincident Peak at DS confluence with WVFKFSHCK
END DESCRIPTION:
DSS Export Rating Curves= 0
DSS Export Rating Curve Sorted= 0
DSS Export Volume Flow Curves= 0
DXF OffsetX= 0
DXF OffsetY= 0
DXF ScaleX= 0
DXF ScaleY= 0

--- LNGDRN.p01 (plan) ---

Plan Title=Floodplain
Program Version=6.30
Short Identifier=Floodplain
Geom File=g01
Flow File=f01
Subcritical Flow
K Sum by GR= 0
Std Step Tol= 0.01
Critical Tol= 0.01
Num of Std Step Trials= 20
Max Error Tol= 0.3
Flow Tol Ratio= 0.001
Split Flow NTrial= 30
Split Flow Tol= 0.02
Split Flow Ratio= 0.02
Log Output Level= 0
Friction Slope Method= 1
Unsteady Friction Slope Method= 2
Unsteady Bridges Friction Slope Method= 1
Parabolic Critical Depth
Global Vel Dist= 0 , 0 , 0
Global Log Level= 0
CheckData=False
Encroach Param=-1 ,0,0, 0
Mapping Interval=1HOUR
Computation Time Step Use Courant=        0
Computation Time Step Use Time Series=    0
Computation Time Step Count To Double=0
Computation Time Step Max Doubling=0
Computation Time Step Max Halving=0
Computation Time Step Residence Courant=0
Run HTab= 0
Run UNet= 0
Run Sediment= 0
Run PostProcess= 0
Run WQNet= 0
Run RASMapper=-1
UNET Theta= 0
UNET Theta Warmup= 0
UNET ZTol= 0
UNET ZSATol= 0
UNET MxIter= 0
UNET Max Iter WO Improvement= 0
UNET MaxInSteps= 0
UNET DtIC= 0
UNET DtMin= 0
UNET MaxCRTS= 0
UNET WFStab= 0
UNET SFStab= 0
UNET WFX= 1
UNET SFX= 1
UNET Gravity=32.17405
UNET 1D Methodology=Finite Difference
UNET DSS MLevel= 1
UNET Pardiso=0
UNET DZMax Abort= 0
UNET Use Existing IB Tables= 0
UNET Froude Reduction=False
UNET Froude Limit= 0
UNET Froude Power= 0
UNET D1 Cores= 0
UNET WindReference=Eulerian
UNET WindDragFormulation=Hsu (1988)
UNET D2 Coriolis=0
UNET D2 Cores= 0
UNET D2 Theta= 1
UNET D2 Theta Warmup= 1
UNET D2 Z Tol= 0.01
UNET D2 Volume Tol= 0.01
UNET D2 Max Iterations= 20
UNET D2 Equation= 0
UNET D2 RampUpFraction=0.1
UNET D2 TimeSlices= 1
UNET D2 Turbulence Formulation=Non-Conservative (original)
UNET D2 Eddy Viscosity=0.3
UNET D2 Transverse Eddy Viscosity=0.1
UNET D2 Smagorinsky Mixing=0
UNET D2 BCVolumeCheck=0
UNET D2 Cores=0
UNET D2 SolverType=PARDISO (Direct)
UNET D2 Minimum Iterations= 3
UNET D2 Maximum Iterations= 30
UNET D2 Restart Number= 10
UNET D2 Relaxation Coeff=1.3
UNET D2 SOR Precondition Iterations= 10
UNET D2 ILUT Maximum Fill= 8
UNET D2 ILUT Tolerance=1E-08
UNET D2 Convergence Tolerance=0.00001
UNET D1D2 MaxIter= 0
UNET D1D2 ZTol=0.01
UNET D1D2 QTol=0.1
UNET D1D2 MinQTol=1
Write IC File= 0
Write IC File at Fixed DateTime=0
Write IC File at Sim End=0
Echo Input=False
Echo Parameters=False
Echo Output=False
Write Detailed= 0
HDF Write Warmup=0
HDF Write Time Slices=0
HDF Flush=0
HDF Compression= 1
HDF Chunk Size= 1
HDF Spatial Parts= 1
HDF Use Max Rows=0
HDF Fixed Rows= 1
Calibration Method= 0
Calibration Iterations= 20
Calibration Max Change=0.05
Calibration Tolerance=0.2
Calibration Maximum=1.5
Calibration Minimum=0.5
Calibration Optimization Method= 1
WQ AD Non Conservative
WQ ULTIMATE=-1
WQ Max Comp Step=1HOUR
WQ Output Interval=15MIN
WQ Output Selected Increments= 0
WQ Output face flow=0
WQ Output face velocity=0
WQ Output face area=0
WQ Output face dispersion=0
WQ Output cell volume=0
WQ Output cell surface area=0
WQ Output cell continuity=0
WQ Output cumulative cell continuity=0
WQ Output face conc=0
WQ Output face dconc_dx=0
WQ Output face courant=0
WQ Output face peclet=0
WQ Output face adv mass=0
WQ Output face disp mass=0
WQ Output cell mass=0
WQ Output cell source sink temp=0
WQ Output nsm pathways=0
WQ Output nsm derived pathways=0
WQ Create Restart=0
WQ Fixed Restart=0
WQ System Summary=0
WQ Write To DSS=0
Sorting and Armoring Iterations= 10
XS Update Threshold= 0.02
Bed Roughness Predictor= 0
Hydraulics Update Threshold= 0.02
Energy Slope Method= 1
Volume Change Method= 1
Sediment Retention Method= 0
Sediment TS Multiplier= 1
Warm Up Method= 0
XS Weighting Method= 0
Number of US Weighted Cross Sections= 1
Number of DS Weighted Cross Sections= 1
Upstream XS Weight=0
Main XS Weight=1
Downstream XS Weight=0
Number of DS XS's Weighted with US Boundary= 1
Upstream Boundary Weight= 1
Weight of XSs Associated with US Boundary= 0
Number of US XS's Weighted with DS Boundary= 1
Downstream Boundary Weight= 0.5
Weight of XSs Associated with DS Boundary= 0.5
Percentile Method= 0
Sediment Output Level= 3
Mass or Volume Output= 0
Output Increment Type= 1
Profile and TS Output Increment= 1
Transport Output Increment 1
XS Output Flag= 0
XS Output Increment= 10
Read HDF5 Sediment Hotstart= 0
Sediment Hotstart Type= 0
Write Gradation File= 0
Read Gradation Hotstart= 0
Write HDF5 File= 1
Write Binary Output= 1
Write DSS Sediment File= 0
DSS Sediment Output Type= 1
SV Curve= 0
Specific Gage Flag= 0
Subcell Erosion Methods= 0
Subcell Deposition Methods= 0
Advection Scheme= 1
Matrix Solver= 0
Implicit Weighting Factor= 1
Maximum Outer Loop Convergence Iterations= 5
Convergence Maximum Absolute= 0.001
Convergence RMSE= 0.0001
Grain Fractions Max Abs Error= 0.001
Max Subgrid Regions= 1
Max Subgrid Length Scale= 3.402823E+38
Initial Layer Thickness= 3.402823E+38
Min Layer Thickness= 3.402823E+38
Max Layer Thickness= 3.402823E+38
Number of Layers= 5

--- LNGDRN.f01 (steady flow) ---

Flow Title=Flow
Program Version=6.30
Number of Profiles= 1
Profile Names=F01pct
River Rch & RM=LNGDRN,Main,46235
     441
River Rch & RM=LNGDRN,Main,44520
     644
River Rch & RM=LNGDRN,Main,42787
     844
River Rch & RM=LNGDRN,Main,40735
    1090
River Rch & RM=LNGDRN,Main,39826
    1570
River Rch & RM=LNGDRN,Main,36644
    1770
River Rch & RM=LNGDRN,Main,35380
    2540
River Rch & RM=LNGDRN,Main,29334
    2880
River Rch & RM=LNGDRN,Main,27985
    3200
River Rch & RM=LNGDRN,Main,20640
    3610
River Rch & RM=LNGDRN,Main,13934
    4030
Boundary for River Rch & Prof#=LNGDRN,Main            , 1
Up Type= 0
Dn Type= 1
Dn Known WS=943.1
DSS Import GetInterval= 0
DSS Import GetPeak= 0
DSS Import FillOption= 0

--- LNGDRN.g01 (geometry) ---

Geom Title=Geometry
Program Version=6.30

River Reach=LNGDRN          ,Main
Reach XY= 30
1699314.44806982406075.490759761     1696528.031      407491.357
     1695258.746      411128.863     1694326.094      412273.334
     1692724.296      413204.498     1692075.003      414734.187
      1692031.94      416089.232     1692931.954      417326.093
     1691314.226       418240.94     1691020.441      419210.332
     1691323.317       421085.96     1690541.487      422167.316
     1690623.784      423515.662     1691285.039      425106.118
     1690477.371      425870.244     1689861.572      425297.508
     1689063.473      425563.063     1687495.143      428799.304
     1686438.973      429174.736     1686622.096      429898.728
     1685544.184      431035.205     1686448.696      431582.582
     1686351.852      432476.375     1686724.681      432912.363
     1685191.643      432538.386     1684665.702      432903.559
     1684489.622      433392.753     1685206.571      433816.874
     1684540.149      435664.1761684652.81828492436396.002181631

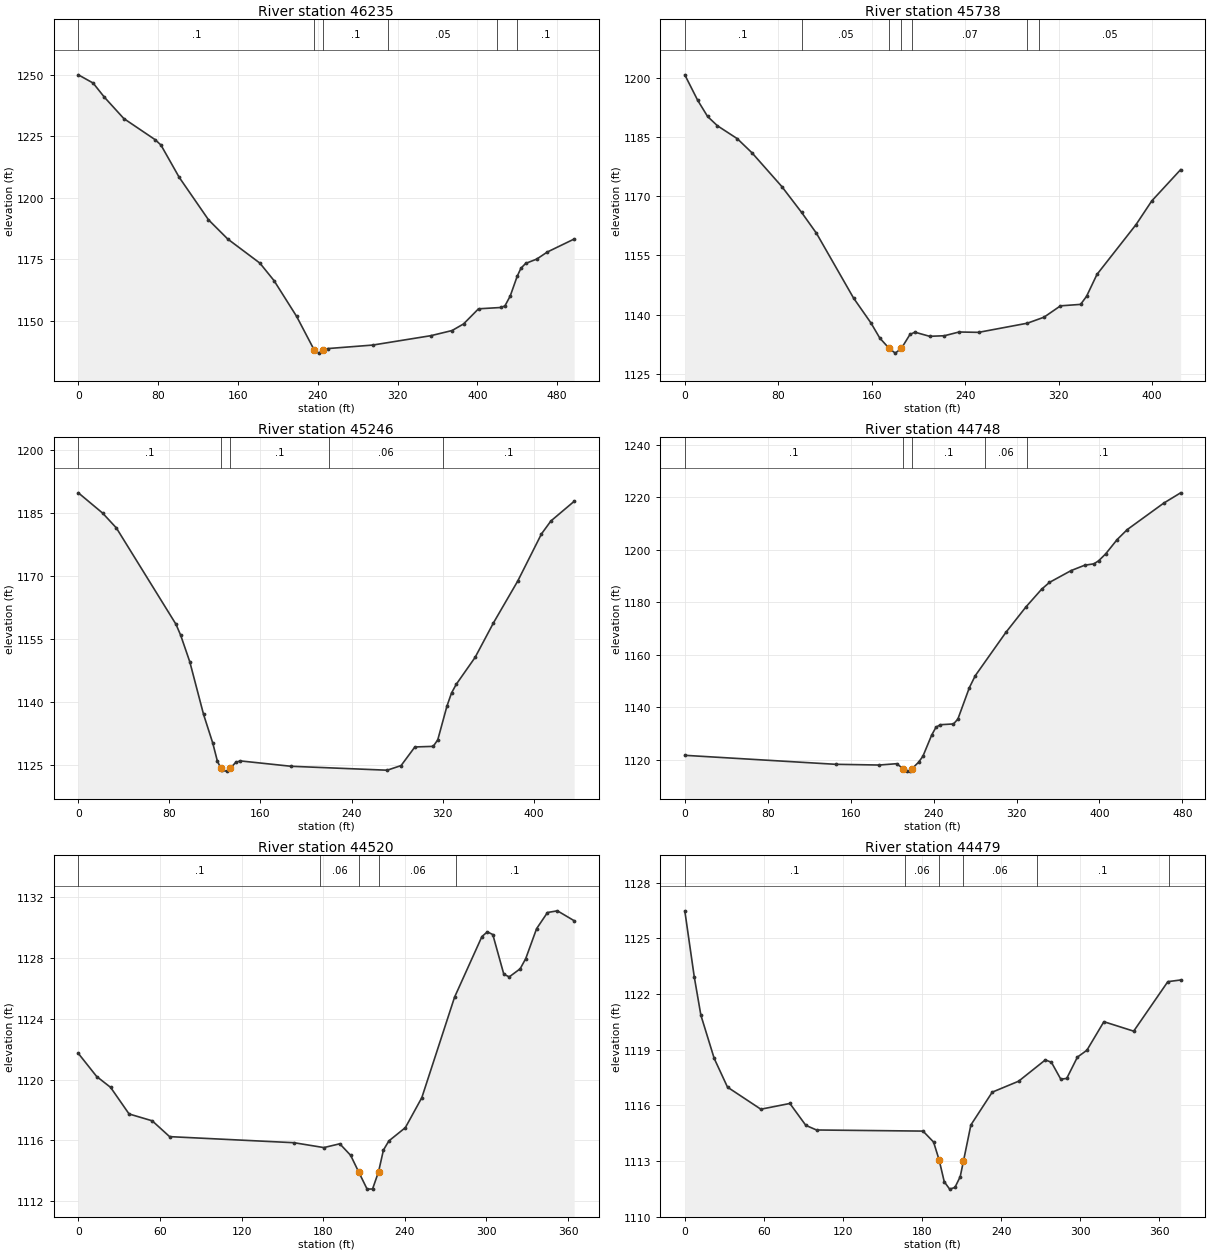
Type RM Length L Ch R = 1 ,46235   ,496.4,496.4,496.4
XS GIS Cut Line= 2
1699113.74968691405938.0611506391699488.39445201406264.800519541
#Sta/Elev= 30
       0 1249.95    14.8 1246.62    26.1 1240.88    45.6  1232.2    76.8 1223.68
    82.8 1221.47   101.1 1208.36   130.5  1191.1   149.8 1183.29     182 1173.52
   196.2 1166.41   218.9 1151.85   236.7 1138.07   241.1 1136.97   245.41138.085
   250.1 1138.82   295.1 1140.24   353.4 1144.05   374.7 1146.14   386.2 1148.82
   401.2 1154.96   423.7  1155.5   427.7 1156.15     433 1160.16     440 1168.18
   443.7 1171.41   448.5  1173.4   459.6 1175.15   470.2 1178.02   497.1 1183.29
#Mann= 6 ,-1,0
       0      .1       0   236.7    .045       0   245.4      .1       0
     310     .05       0     420     .06       0     440      .1       0
Bank Sta=236.7,245.4
XS Rating Curve= 0 ,0
Exp/Cntr(USF)=0,0
Exp/Cntr=0.3,0.1

Type RM Length L Ch R = 1 ,45738   ,492.1,492.1,492.1
XS GIS Cut Line= 4
1698854.19035944406226.1803234321698901.94835441406362.489600751
1698943.73660001406494.8190451561699036.26771527406601.279575618
#Sta/Elev= 30
       0  1200.7      11 1194.27    19.5 1190.16    27.9 1187.81    44.9 1184.54
    57.6 1180.93      83 1172.43     100 1165.85   112.7 1160.58   144.4  1144.2
   159.2 1137.93   166.9 1134.05   174.9 1131.45   180.1 1130.25   185.31131.431
   192.7 1134.98   196.9 1135.55   209.5 1134.51   222.1 1134.65   234.7  1135.6
   251.4 1135.51   293.2 1137.83   307.4 1139.35   321.5 1142.22   338.7 1142.59
   343.8 1144.63   352.7 1150.17   386.2 1162.81   399.6 1168.78   424.3  1176.7
#Mann= 7 ,-1,0
       0      .1       0     100     .05       0   174.9    .045       0
   185.3     .05       0  194.43     .07       0   293.2     .06       0
   303.2     .05       0
Bank Sta=174.9,185.3
XS Rating Curve= 0 ,0
Exp/Cntr(USF)=0,0
Exp/Cntr=0.3,0.1

Type RM Length L Ch R = 1 ,45246   ,498.2,498.2,498.2
XS GIS Cut Line= 3
1698409.13694538406299.414162431 1698452.1289676406631.066905301
1698480.38086792406728.106041178
#Sta/Elev= 30
       0 1189.86    21.3 1185.03    33.4 1181.48    85.8 1158.47    89.9 1155.86
    97.9 1149.52     110 1136.96   118.1  1130.1   122.1 1125.85   125.1 1124.16
   126.2 1123.59   130.2 1123.43   133.5 1124.13   138.3 1125.53   142.3 1125.87
   186.7 1124.59   271.3 1123.65   283.5 1124.76   295.6  1129.2   311.7 1129.34
   315.7  1130.9   323.8 1138.98   327.8 1142.09   331.9 1144.14   348.5 1150.58
   364.6 1158.81     386 1168.83   406.8 1180.06   415.1 1183.15   435.5 1187.83
#Mann= 5 ,-1,0
       0      .1       0   125.1    .045       0   133.5      .1       0
     220     .06       0     320      .1       0
Bank Sta=125.1,133.5
XS Rating Curve= 0 ,0
Exp/Cntr(USF)=0,0
Exp/Cntr=0.3,0.1

Type RM Length L Ch R = 1 ,44748   ,228,228,228
XS GIS Cut Line= 3
1698059.53035322 406438.415129571698178.92534066406800.579924784
1698222.70350271406887.141290673
#Sta/Elev= 30
       0 1121.73   145.4 1118.31   187.6 1118.03   204.4 1118.54   210.81116.572
   214.4 1115.71     217  1115.8   219.1 1116.61   225.5 1119.09   229.7 1121.38
   238.1 1129.39   242.3 1132.42   246.5 1133.38   259.2 1133.68   263.4 1135.51
   274.5  1147.5   280.2 1152.05   309.7 1168.52   329.1 1178.24   344.2 1184.97
   351.8 1187.58   372.7 1192.08   385.8 1194.12   394.7 1194.65   399.2  1195.8
     406 1198.44   417.1  1203.9   426.8 1207.68     462 1217.76   478.3 1221.68
#Mann= 5 ,-1,0
       0      .1       0   210.8    .045       0   219.1      .1       0
     290     .06       0     330      .1       0
Bank Sta=210.8,219.1
XS Rating Curve= 0 ,0
Exp/Cntr(USF)=0,0
Exp/Cntr=0.3,0.1

Type RM Length L Ch R = 1 ,44520   ,41.5,41.5,41.5
XS GIS Cut Line= 3
1697958.01603942406550.0142974461697909.37363713406610.817300305
1697938.11687485406896.038659172
#Sta/Elev= 30
       0 1121.72    13.5  1120.2    23.7 1119.49    37.3 1117.74    54.3 1117.29
    67.1 1116.25   158.6 1115.85   180.5 1115.53   192.2 1115.78   200.2 1115.02
     2061113.946   212.3  1112.8   216.3 1112.81   220.7 1113.94   224.3 1115.37
   228.3 1115.97   240.4 1116.84   252.5 1118.81   276.6 1125.42   296.7  1129.4
   300.7 1129.71   304.7 1129.53   312.8 1126.92   316.8 1126.75   324.8 1127.28
   328.9 1127.95   336.9 1129.92   344.9 1130.98   352.2 1131.09   364.5 1130.44
#Mann= 5 ,-1,0
       0      .1       0  177.87     .06       0     206    .045       0
   220.7     .06       0  277.87      .1       0
Bank Sta=206,220.7
XS Rating Curve= 0 ,0
Exp/Cntr(USF)=0,0
Exp/Cntr=0.3,0.1

Type RM Length L Ch R = 1 ,44479   ,237.2,237.2,237.2
XS GIS Cut Line= 3
1697903.84609142406558.8583705891697862.94225313406611.922809448
1697904.95160056 406918.14884203
#Sta/Elev= 30
       0 1126.49     7.2 1122.92    12.2 1120.86    22.3 1118.53    32.4 1116.98
    57.7 1115.79    79.7  1116.1    91.8 1114.92    99.9 1114.67   180.7 1114.61
   188.7 1114.02   192.9 1113.06   196.8 1111.88   200.9 1111.48   204.9 1111.57
   208.9 1112.15   211.4    1113     217 1114.94   233.2 1116.71   253.2  1117.3
   273.5 1118.45   278.1 1118.32   285.2 1117.41   289.7 1117.45   297.8  1118.6
     305 1118.97   317.9 1120.51   340.5    1120   366.4 1122.67   376.1 1122.76
#Mann= 6 ,-1,0
       0      .1       0     167     .06       0   192.9    .045       0
   211.4     .06       0     267      .1       0     367     .06       0
Bank Sta=192.9,211.4
XS Rating Curve= 0 ,0
Exp/Cntr(USF)=0,0
Exp/Cntr=0.3,0.1

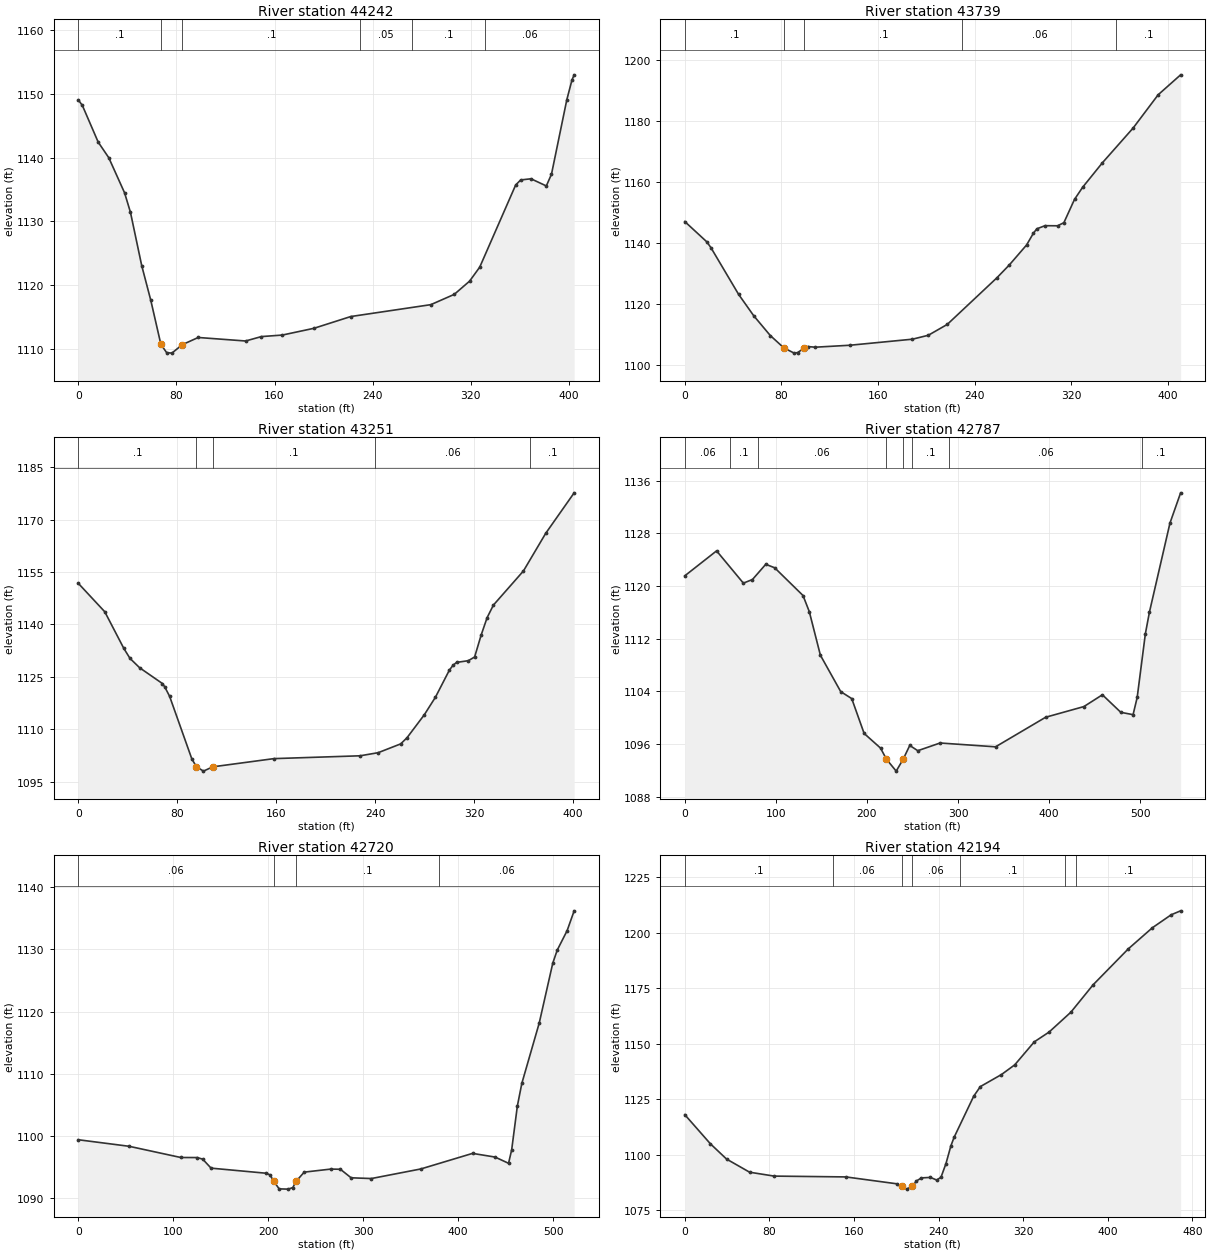
Type RM Length L Ch R = 1 ,44242   ,502.2,502.2,502.2
XS GIS Cut Line= 3
1697672.19778721406593.4532587211697763.64113607406828.203348324
1697807.31557134406974.239741275
#Sta/Elev= 30
       0 1149.02     3.3 1148.15    16.2 1142.41    24.8 1139.98    37.7 1134.48
    42.5 1131.43    51.7 1123.07    59.1 1117.64    67.31110.764      72 1109.45
    76.3 1109.37    84.81110.696    97.8 1111.82   136.4 1111.27   149.3 1111.96
   166.4  1112.2   192.2 1113.26   222.2  1115.1   287.5 1116.96   306.6 1118.57
   319.1 1120.64   327.4 1122.84   356.7  1135.7   360.8 1136.49   369.2 1136.67
   381.7 1135.55   385.9 1137.38   398.4 1149.04   402.6 1152.13   404.4 1152.95
#Mann= 6 ,-1,0
       0      .1       0    67.3    .045       0    84.8      .1       0
     230     .05       0  271.93      .1       0  331.93     .06       0
Bank Sta=67.3,84.8
XS Rating Curve= 0 ,0
Exp/Cntr(USF)=0,0
Exp/Cntr=0.3,0.1

Type RM Length L Ch R = 1 ,43739   ,488.2,488.2,488.2
XS GIS Cut Line= 3
1697279.03390663406941.5461963211697457.14371299407113.514285216
1697561.55290982407238.805321412
#Sta/Elev= 30
       0    1147    18.2 1140.38    21.6 1138.49    44.6 1123.17    57.1 1116.19
    70.8 1109.73    82.1 1105.67    90.6 1103.97    93.4 1104.15    99.1 1105.62
   101.9 1106.12     108 1105.91   136.8 1106.55   188.6 1108.53   201.7 1109.81
   217.4 1113.36   258.5  1128.6   268.9 1132.85   283.1 1139.34   288.8 1143.22
   291.6 1144.63   298.4 1145.65   308.8 1145.62     314 1146.63   322.8 1154.25
   329.6 1158.25   345.9 1166.22   371.3 1177.56   392.1 1188.47   410.7 1194.99
#Mann= 5 ,-1,0
       0      .1       0    82.1    .045       0    99.1      .1       0
     230     .06       0  357.58      .1       0
Bank Sta=82.1,99.1
XS Rating Curve= 0 ,0
Exp/Cntr(USF)=0,0
Exp/Cntr=0.3,0.1

Type RM Length L Ch R = 1 ,43251   ,464.1,464.1,464.1
XS GIS Cut Line= 3
1696900.89759144407194.2655809791697044.96256891407429.318965272
1697122.30271471 407527.88973933
#Sta/Elev= 30
       0 1151.74    21.4  1143.6    36.8 1133.11    41.8 1130.25    49.6 1127.57
      68 1123.06    69.9 1122.09    73.8 1119.42    91.8 1101.47    95.51099.237
   101.2 1097.98   108.7 1099.21   158.2 1101.56   227.9 1102.37   242.5 1103.26
   260.7 1105.78   265.8 1107.53   279.8 1114.11   288.8 1119.14   300.1 1126.91
     303 1128.27   305.9 1129.11   315.4  1129.6   320.5 1130.66   325.8 1136.96
   330.6 1141.92   335.7 1145.52     360  1155.3     378 1166.07     401 1177.66
#Mann= 5 ,-1,0
       0      .1       0    95.5    .045       0   108.7      .1       0
     240     .06       0  365.69      .1       0
Bank Sta=95.5,108.7
XS Rating Curve= 0 ,0
Exp/Cntr(USF)=0,0
Exp/Cntr=0.3,0.1

Type RM Length L Ch R = 1 ,42787   ,67.1,67.1,67.1
XS GIS Cut Line= 3
1696351.71125479407349.2974077591696589.39572052407518.440306621
1696705.47418052407742.858662629
#Sta/Elev= 30
       0 1121.55    34.9 1125.34    64.3 1120.44    74.3 1120.99    88.9  1123.3
    98.7 1122.77   129.8 1118.56   136.7 1116.11   148.9 1109.49   171.2 1103.97
   183.3 1102.91   196.9 1097.62   214.9  1095.4   221.4 1093.71   232.1  1091.9
   239.71093.689     247  1095.8   255.8    1095   280.3 1096.17   341.2 1095.59
   396.2 1100.08   438.2  1101.7   458.5 1103.49   478.7 1100.83   492.2 1100.47
   496.7 1103.08   505.7 1112.76   510.2 1116.07   532.7 1129.56   544.4 1134.15
#Mann= 8 ,-1,0
       0     .06       0      50      .1       0      80     .06       0
   221.4    .045       0   239.7     .06       0     250      .1       0
     290     .06       0  501.72      .1       0
Bank Sta=221.4,239.7
XS Rating Curve= 0 ,0
Exp/Cntr(USF)=0,0
Exp/Cntr=0.3,0.1

Type RM Length L Ch R = 1 ,42720   ,525.6,525.6,525.6
XS GIS Cut Line= 3
 1696311.4491607407411.6999610221696528.12895271407554.310640456
1696663.00106814407779.834505606
#Sta/Elev= 30
       0 1099.42    53.5 1098.37   107.9 1096.57   125.3 1096.56     131  1096.3
   139.8 1094.86     198 1094.04   201.9 1093.77   205.7 1092.78   211.5 1091.53
   221.1 1091.49   225.9 1091.74   229.2 1092.72   237.9 1094.22   265.9 1094.71
     276 1094.68   287.3 1093.31   308.6 1093.19   360.7 1094.73   415.2 1097.23
   438.9 1096.64   453.1 1095.64   456.4 1097.81   462.4 1104.86   467.1 1108.48
   485.4 1118.16   499.7  1127.8   504.4 1129.89   514.8 1133.01   522.2 1136.19
#Mann= 4 ,-1,0
       0     .06       0   205.7    .045       0   229.2      .1       0
   379.4     .06       0
Bank Sta=205.7,229.2
XS Rating Curve= 0 ,0
Exp/Cntr(USF)=0,0
Exp/Cntr=0.3,0.1

Type RM Length L Ch R = 1 ,42194   ,527.4,527.4,527.4
XS GIS Cut Line= 3
1696171.29810237407903.2700709311696531.69408296408115.527826368
1696574.80893953408142.060045797
#Sta/Elev= 30
       0 1118.07    24.2 1104.97    39.5  1098.1    61.3 1092.19    84.5 1090.44
   152.3 1090.07   200.6 1086.97   205.2 1085.94   209.8 1084.58   215.3 1085.93
   219.1 1088.26   223.8 1089.63   232.3 1089.85   238.2 1088.67   242.3 1089.94
     247 1096.09   251.6 1103.99   254.7 1107.91   273.2 1126.36   279.5  1130.7
   299.5 1136.13     312 1140.47   330.5 1150.82   344.5 1155.23   365.1 1164.16
   386.2 1176.52   419.3  1192.6   442.2 1202.15     460 1207.99   468.9 1209.76
#Mann= 7 ,-1,0
       0      .1       0     140     .06       0   205.2    .045       0
   215.3     .06       0     260      .1       0     360     .06       0
     370      .1       0
Bank Sta=205.2,215.3
XS Rating Curve= 0 ,0
Exp/Cntr(USF)=0,0
Exp/Cntr=0.3,0.1

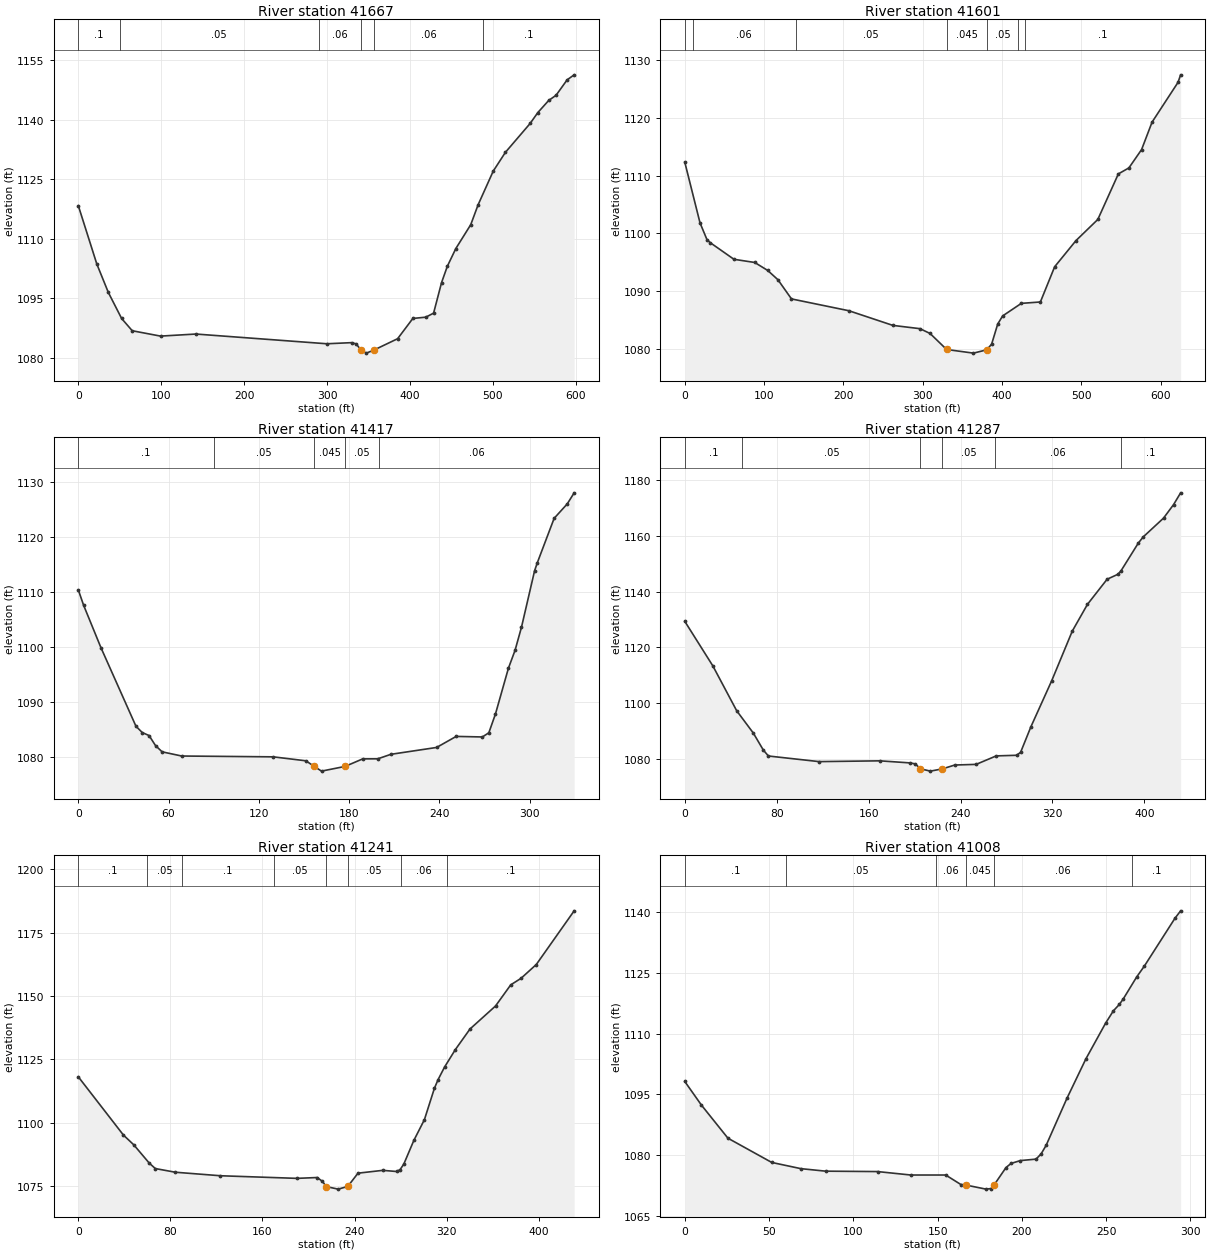
Type RM Length L Ch R = 1 ,41667   ,65.6,65.6,65.6
XS GIS Cut Line= 3
 1695994.4573963408143.5990151941696143.47519548408545.197159023
1696295.70380445408619.819026168
#Sta/Elev= 30
       0 1118.34    22.3 1103.65    36.2 1096.48    52.2 1089.93      65 1086.84
    99.1 1085.49   141.8 1086.01   299.7 1083.56   329.5 1083.84     335 1083.53
     3411081.959   347.4  1081.2   356.8 1082.01     385 1084.83   403.4 1089.94
     419 1090.26   428.4 1091.28     438 1098.97     445  1103.1   455.2 1107.55
   473.2 1113.57   482.1 1118.59   500.3 1127.06     515  1131.8   544.8 1139.07
   554.1 1141.82   567.2 1144.87   576.1 1146.18   589.4 1150.06   597.9 1151.33
#Mann= 6 ,-1,0
       0      .1       0      50     .05       0     290     .06       0
     341    .045       0   356.8     .06       0  488.35      .1       0
Bank Sta=341,356.8
XS Rating Curve= 0 ,0
Exp/Cntr(USF)=0,0
Exp/Cntr=0.3,0.1

Type RM Length L Ch R = 1 ,41601   ,184.3,184.3,184.3
XS GIS Cut Line= 3
1695949.61562987408178.3721506011696097.70103578408580.396086804
1696274.80360047408665.962494464
#Sta/Elev= 30
       0  1112.3    19.2 1101.78    27.9  1098.9    32.1 1098.35      62 1095.47
    88.2 1094.92   104.6 1093.53   117.4 1091.93   134.5  1088.6   206.9 1086.55
   262.3 1084.01   296.5 1083.44   309.2 1082.61   330.1 1079.83   363.9  1079.2
   380.6 1079.77   386.8 1080.75   394.5 1084.24   400.7 1085.65   424.3 1087.83
   448.3 1088.07   466.3 1094.18   493.2 1098.72   520.7 1102.38   546.6 1110.28
   559.9 1111.32   575.9  1114.5   589.1 1119.26   621.8 1126.15   625.1 1127.46
#Mann= 7 ,-1,0
       0      .1       0      10     .06       0     140     .05       0
   330.1    .045       0   380.6     .05       0     420     .06       0
  428.43      .1       0
Bank Sta=330.1,380.6
XS Rating Curve= 0 ,0
Exp/Cntr(USF)=0,0
Exp/Cntr=0.3,0.1

Type RM Length L Ch R = 1 ,41417   ,130.4,130.4,130.4
XS GIS Cut Line= 2
1695820.84976941408604.0785246451696124.31202914408732.428136136
#Sta/Elev= 30
       0 1110.32     3.5 1107.54      15 1099.83    38.3 1085.51    42.5 1084.36
      47 1083.82    51.3 1081.99    55.7 1080.85    68.7 1080.09   129.5 1079.94
   151.2 1079.22   156.71078.213   161.6 1077.34   177.3  1078.2     189 1079.57
     199 1079.58   207.7  1080.4   238.1 1081.65   251.1 1083.66   268.5 1083.56
   272.8 1084.32   277.2 1087.74   285.8 1096.06   290.2 1099.31   294.5 1103.54
   303.2 1113.81     305 1115.26   316.2 1123.36   324.9 1125.98   329.5    1128
#Mann= 5 ,-1,0
       0      .1       0      90     .05       0   156.7    .045       0
   177.3     .05       0     200     .06       0
Bank Sta=156.7,177.3
XS Rating Curve= 0 ,0
Exp/Cntr(USF)=0,0
Exp/Cntr=0.3,0.1

Type RM Length L Ch R = 1 ,41287   ,45.5,45.5,45.5
XS GIS Cut Line= 2
1695758.01010558408694.6437093221696149.66381972408875.956060579
#Sta/Elev= 30
       0 1129.35    24.4 1113.39    45.2 1097.28    59.6 1089.33    68.4 1083.18
    72.8 1081.08   116.9 1079.07   169.8 1079.35   196.3  1078.6   200.7 1078.24
   205.1 1076.49   213.8 1075.66   224.31076.473     235 1077.85   253.6 1078.08
   271.1 1081.12   288.8 1081.34   292.3  1082.4   301.3 1091.58   319.4 1108.08
   337.3 1125.86   350.5 1135.44   367.6 1144.44     377 1146.22   379.6 1147.39
   394.7 1157.36     399  1159.6   416.7 1166.34   425.5 1171.22   431.6 1175.42
#Mann= 6 ,-1,0
       0      .1       0      50     .05       0   205.1    .045       0
   224.3     .05       0     270     .06       0     380      .1       0
Bank Sta=205.1,224.3
XS Rating Curve= 0 ,0
Exp/Cntr(USF)=0,0
Exp/Cntr=0.3,0.1

Type RM Length L Ch R = 1 ,41241   ,232.6,232.6,232.6
XS GIS Cut Line= 2
1695748.47433491408735.942396692 1696137.8592219408920.193920508
#Sta/Elev= 30
       0 1118.03    39.2 1095.04    48.2 1091.19    61.6 1083.99    66.9 1081.83
    84.3 1080.38   123.5 1078.99   189.9 1077.96   207.6 1078.29     212 1076.79
   215.6 1074.69   225.8 1073.71   234.1 1074.77     243 1080.01   264.5 1081.12
   276.5 1080.67   279.5 1081.36   282.8 1083.61   291.5 1092.93   300.7 1101.14
   309.4 1113.55   312.6 1116.96   318.2  1121.9   327.6 1128.81   340.3 1136.92
   362.5 1146.01   375.7 1154.35   384.6 1156.91   397.9 1162.38   430.8 1183.57
#Mann= 8 ,-1,0
       0      .1       0      60     .05       0      90      .1       0
     170     .05       0   215.6    .045       0   234.1     .05       0
     280     .06       0     320      .1       0
Bank Sta=215.6,234.1
XS Rating Curve= 0 ,0
Exp/Cntr(USF)=0,0
Exp/Cntr=0.3,0.1

Type RM Length L Ch R = 1 ,41008   ,274,274,274
XS GIS Cut Line= 4
1695678.13233025408939.1739655351695744.79453156408981.957169365
1695875.13405951409048.6193706821695934.83155323409082.447950455
#Sta/Elev= 30
       0  1098.2     9.9 1092.36    25.6 1084.21    51.6 1078.23    68.9  1076.7
    83.6 1076.08   114.4 1075.98   134.1 1075.13   154.8 1075.13   163.8 1072.79
   166.71072.663   178.7 1071.65   181.7 1071.79   183.41072.606   190.6 1076.98
   193.6 1077.99   199.1 1078.69   208.4 1079.05   211.4 1080.33   214.4 1082.45
   226.7 1094.01     238 1103.79   249.7  1112.6   254.3 1115.63   257.9 1117.24
   260.3 1118.66   268.1 1123.97   272.7 1126.68   290.8 1138.44   294.2  1140.3
#Mann= 6 ,-1,0
       0      .1       0      60     .05       0  149.21     .06       0
   166.7    .045       0   183.4     .06       0  265.61      .1       0
Bank Sta=166.7,183.4
XS Rating Curve= 0 ,0
Exp/Cntr(USF)=0,0
Exp/Cntr=0.3,0.1

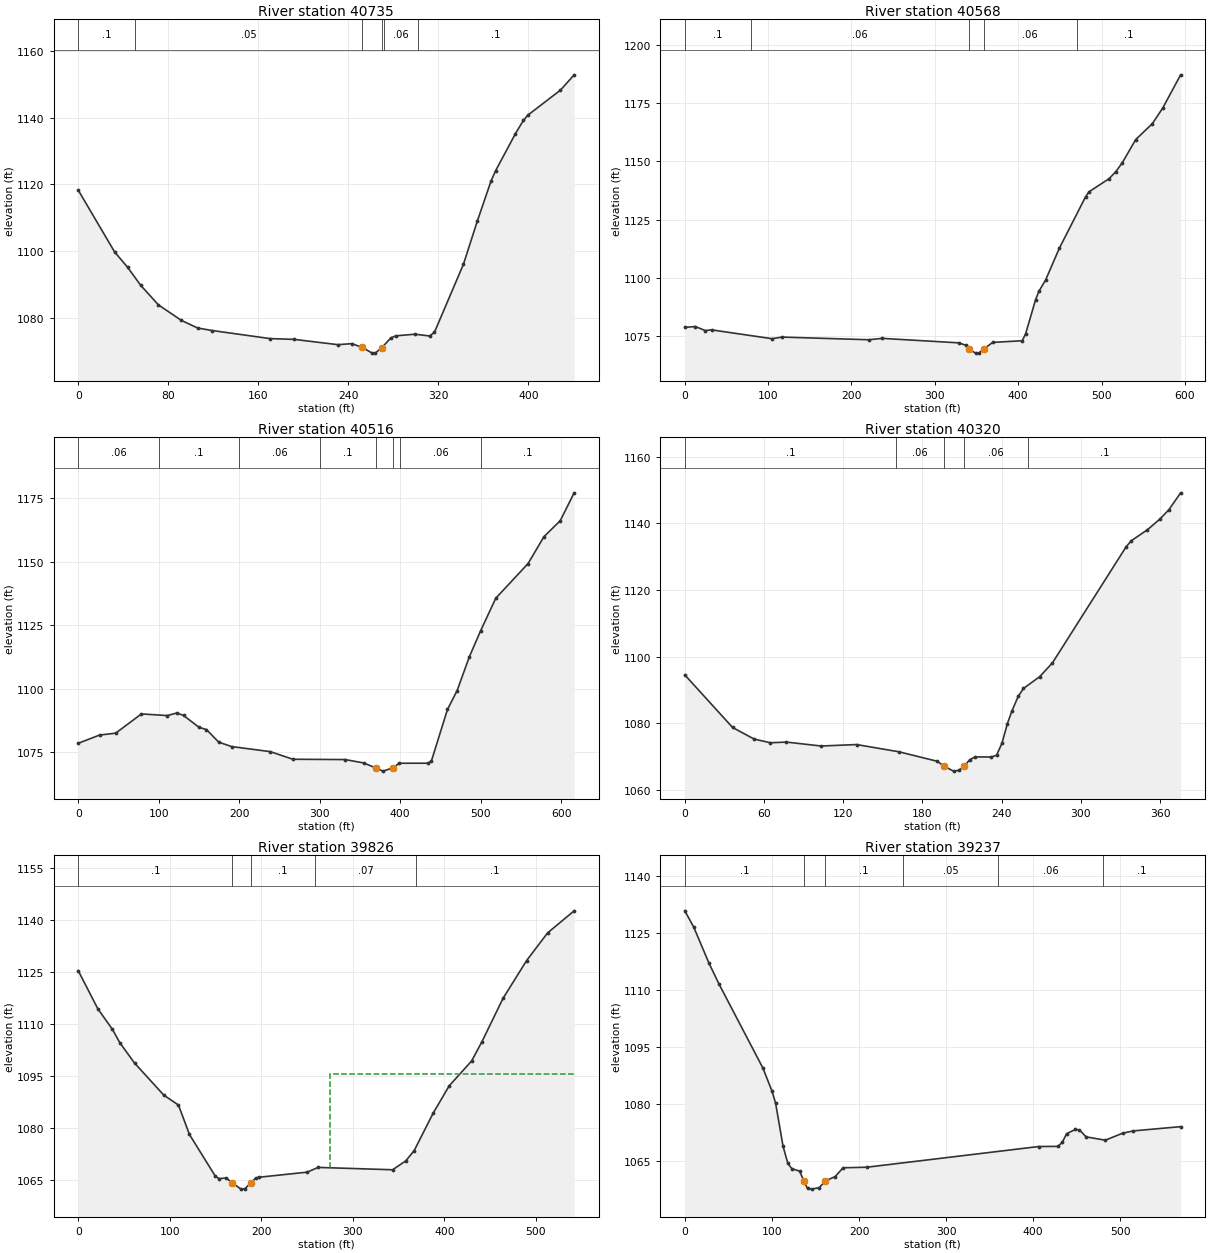
Type RM Length L Ch R = 1 ,40735   ,167,167,167
XS GIS Cut Line= 4
1695472.99568137409125.9885485231695538.66292446409189.665875154
1695772.47810818409281.2020321861695867.99409813409303.091113216
#Sta/Elev= 30
       0 1118.18    32.2  1099.7    43.9 1095.02    55.4 1089.67    71.2 1083.78
    91.5 1079.15   105.9 1076.86   118.8  1076.1   170.4 1073.67   191.8 1073.44
   230.5 1071.85     243 1072.15   252.41071.013   260.6 1069.41   263.9 1069.31
   269.81070.995   277.7 1073.87     282  1074.5   299.2 1074.99   312.1 1074.46
   316.4 1075.53   342.2 1095.97   354.5 1108.89   366.8 1121.03   370.9 1124.12
   388.4 1135.17   395.5 1139.17   399.6 1140.78   428.4 1148.24   440.6 1152.84
#Mann= 6 ,-1,0
       0      .1       0      50     .05       0   252.4    .045       0
   269.8     .05       0  271.47     .06       0  301.47      .1       0
Bank Sta=252.4,269.8
XS Rating Curve= 0 ,0
Exp/Cntr(USF)=0,0
Exp/Cntr=0.3,0.1

Type RM Length L Ch R = 1 ,40568   ,52,52,52
XS GIS Cut Line= 2
1695331.50639042409426.1248799221695925.96398166409403.377778217
#Sta/Elev= 30
       0 1078.64    12.6    1079    24.6 1077.26    32.3 1077.56   104.7 1073.76
   116.7 1074.46   220.8 1073.32   236.8 1073.91   328.8 1071.98   336.9 1070.98
   340.9 1069.17   349.1 1067.56     353 1067.63   358.71069.297   369.4 1072.18
   404.9 1072.89   408.9 1075.85   420.9 1090.57   424.9 1094.17   432.9    1099
   449.3 1112.63     481 1134.91     485 1136.96     509 1142.59     517 1145.57
     525  1149.5     541 1159.42     561 1166.27   573.4 1172.97   594.9 1187.27
#Mann= 5 ,-1,0
       0      .1       0      80     .06       0   340.9    .045       0
   358.7     .06       0     470      .1       0
Bank Sta=340.9,358.7
XS Rating Curve= 0 ,0
Exp/Cntr(USF)=0,0
Exp/Cntr=0.3,0.1

Type RM Length L Ch R = 1 ,40516   ,195.1,195.1,195.1
XS GIS Cut Line= 2
1695305.72634182409477.6849771221695921.41456132409454.937875416
#Sta/Elev= 30
       0 1078.61    26.4 1081.83    46.4 1082.57    78.4 1090.13   110.5 1089.49
   122.5 1090.51   130.8 1089.52   150.1 1084.84   159.2 1083.99   174.5 1079.03
   190.5 1077.31   238.6 1075.31   266.6 1072.32   331.5  1072.2   354.7 1070.87
   370.1 1068.82   378.6 1067.66   390.7 1068.91   398.7 1070.76   434.7 1070.77
   438.7 1071.62   458.7  1091.9   470.7 1099.31   485.9 1112.61     500 1122.89
   518.7 1135.58   558.8 1149.19   578.6 1159.78   598.8 1166.04   616.1 1176.99
#Mann= 8 ,-1,0
       0     .06       0     100      .1       0     200     .06       0
     300      .1       0   370.1    .045       0   390.7      .1       0
     400     .06       0     500      .1       0
Bank Sta=370.1,390.7
XS Rating Curve= 0 ,0
Exp/Cntr(USF)=0,0
Exp/Cntr=0.3,0.1

Type RM Length L Ch R = 1 ,40320   ,494.3,494.3,494.3
XS GIS Cut Line= 2
1695544.61478797409688.9061945391695912.74933256409614.837081965
#Sta/Elev= 30
       0 1094.57    36.2  1078.8    52.5 1075.33    64.8 1074.22      77 1074.42
   103.3 1073.24   130.1 1073.68   162.3  1071.5   191.3 1068.65     1961067.269
   203.5 1065.71   207.6 1065.95   211.7 1067.23   215.7  1069.1   219.8 1069.97
   232.1 1069.95   236.1 1070.46   240.2 1074.08   244.3 1079.95   247.8 1083.79
   252.5 1088.13   256.5 1090.51   268.8 1094.05   278.4 1098.16   334.1 1132.91
   338.1  1134.8   350.4 1138.11   359.9 1141.34   366.7 1144.16   375.5 1149.18
#Mann= 5 ,-1,0
       0      .1       0     160     .06       0     196    .045       0
   211.7     .06       0     260      .1       0
Bank Sta=196,211.7
XS Rating Curve= 0 ,0
Exp/Cntr(USF)=0,0
Exp/Cntr=0.3,0.1

Type RM Length L Ch R = 1 ,39826   ,589.2,589.2,589.2
XS GIS Cut Line= 4
 1695646.8218266410128.662506941 1695765.5616975 410134.12181135
1695925.24635147410119.1087242241696139.52404954409967.613026864
#Sta/Elev= 30
       0 1125.37    21.3 1114.39    37.3 1108.42    45.3 1104.59    61.4  1098.7
    93.4 1089.41   109.4 1086.54   121.4 1078.03   149.6 1065.99   153.6 1065.26
   161.6 1065.44   168.21064.026   177.7 1062.22   181.7 1062.29   188.8 1064.11
   193.7 1065.41   197.8 1065.67     250 1067.13     262  1068.5   343.4 1067.82
   357.8 1070.42   366.9 1073.36   387.6 1084.17   405.2 1092.12   429.7  1099.3
     441  1104.9     464 1117.41   489.8 1128.36   512.7 1136.35   541.7 1142.73
#Mann= 5 ,-1,0
       0      .1       0   168.2    .045       0   188.8      .1       0
  258.87     .07       0  369.25      .1       0
#XS Ineff= 2 , 0
                           275.2          1095.5
Permanent Ineff=
       F       F
Bank Sta=168.2,188.8
XS Rating Curve= 0 ,0
Exp/Cntr(USF)=0,0
Exp/Cntr=0.3,0.1

Type RM Length L Ch R = 1 ,39237   ,514.2,514.2,514.2
XS GIS Cut Line= 3
1695383.53552848410515.772758617 1695737.3793328410702.991702698
1695874.04916198 410802.21774306
#Sta/Elev= 30
       0 1130.96    10.2  1126.7    27.8 1117.16    39.5  1111.6    89.8 1089.52
   100.2 1083.45   104.3 1080.28   112.8 1068.99   118.3  1064.5   122.8 1063.11
   131.9 1062.45   136.5 1059.94   140.9 1057.89   145.5 1057.72   154.5 1058.11
   160.8  1059.8   172.6 1061.03   181.7 1063.34   208.8 1063.48   406.2 1068.93
   428.4 1068.97   433.4 1070.06   438.3 1072.29   448.2 1073.42   453.1 1073.29
   460.7 1071.47   482.8  1070.6   502.6 1072.44   515.1 1073.05   569.2 1074.16
#Mann= 6 ,-1,0
       0      .1       0   136.5    .045       0   160.8      .1       0
     250     .05       0     360     .06       0  480.32      .1       0
Bank Sta=136.5,160.8
XS Rating Curve= 0 ,0
Exp/Cntr(USF)=0,0
Exp/Cntr=0.3,0.1

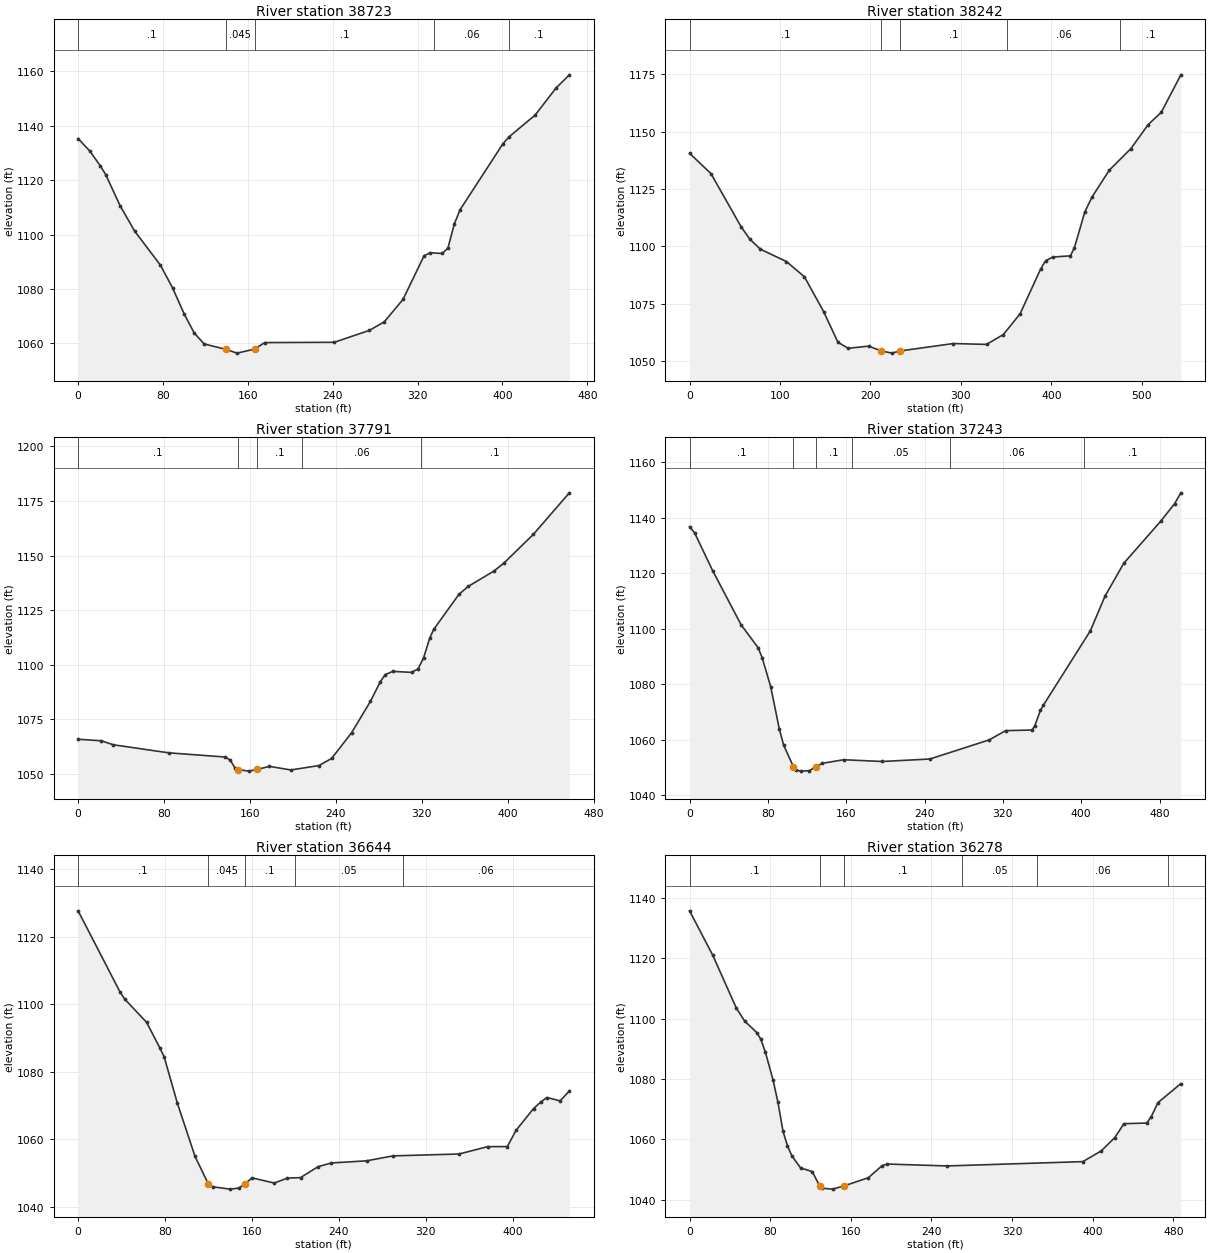
Type RM Length L Ch R = 1 ,38723   ,480.4,480.4,480.4
XS GIS Cut Line= 4
1695179.14026369410949.2652219941695261.02982983411008.407686429
1695426.32543556411111.5278808291695546.12683788411228.296336252
#Sta/Elev= 30
       0 1135.31    11.1  1130.7    20.9 1125.29      26  1122.1    39.7 1110.54
    53.4 1101.25    77.5 1088.83      89 1080.48    99.9  1070.9   109.4 1063.88
   118.8  1059.8     139 1057.86   149.8 1056.43   166.3  1057.9   175.9  1060.3
   241.4 1060.41   274.4 1064.77   288.5 1067.88   306.3  1076.2   326.1  1092.2
   331.8 1093.34   343.1 1093.07   348.6 1095.02   354.6 1103.86     360 1109.11
   400.4 1133.37   406.2 1135.95   430.8 1143.94   450.6 1153.93   463.1 1158.75
#Mann= 5 ,-1,0
       0      .1       0     139    .045       0   166.3      .1       0
  335.84     .06       0  405.84      .1       0
Bank Sta=139,166.3
XS Rating Curve= 0 ,0
Exp/Cntr(USF)=0,0
Exp/Cntr=0.3,0.1

Type RM Length L Ch R = 1 ,38242   ,451.4,451.4,451.4
XS GIS Cut Line= 4
1694875.84557428411160.055031134 1694944.0868794 411260.14227864
 1695124.5472196411467.8991408861695204.92031229411590.733490097
#Sta/Elev= 30
       0 1140.59    23.6 1131.74    57.3 1108.36    66.7 1103.15    78.3  1098.8
   107.1 1093.43     127 1086.77   148.2 1071.61     164 1058.28   175.3 1055.65
     198 1056.58   211.7 1054.54   223.5 1053.54   232.9  1054.5   291.6 1057.72
   328.3 1057.34   346.9 1061.65   365.4 1070.68     388  1090.1   393.6  1093.8
   401.9 1095.41     421 1095.92   425.4 1099.42   436.9 1115.01   444.9 1121.54
     464 1133.23   487.9 1142.63     507 1153.09   521.4 1158.39   543.1 1174.75
#Mann= 5 ,-1,0
       0      .1       0   211.7    .045       0   232.9      .1       0
  351.14     .06       0  476.33      .1       0
Bank Sta=211.7,232.9
XS Rating Curve= 0 ,0
Exp/Cntr(USF)=0,0
Exp/Cntr=0.3,0.1

Type RM Length L Ch R = 1 ,37791   ,547.9,547.9,547.9
XS GIS Cut Line= 4
1694644.17495894411516.8919347531694716.51074237411583.768413768
1694873.46574414411650.6448927831695037.24487642411743.453067743
#Sta/Elev= 30
       0 1065.86    21.7 1065.16    32.6 1063.34    84.6 1059.62   137.2 1057.71
   141.6 1056.32   145.9 1052.85   148.61051.992     159 1051.25   166.91052.052
   178.1 1053.43   198.1 1051.79   224.2  1053.8     236 1057.04   254.6 1068.81
   272.2 1083.24   281.4 1092.23     286 1095.49     293 1096.95   310.6 1096.49
   316.5 1098.12   321.6 1103.01   327.3 1112.09   331.1 1116.21   354.6 1132.27
   363.4 1135.93   387.1  1142.9   396.3  1146.5   423.9 1159.75   457.4 1178.76
#Mann= 5 ,-1,0
       0      .1       0   148.6    .045       0   166.9      .1       0
  208.51     .06       0  319.12      .1       0
Bank Sta=148.6,166.9
XS Rating Curve= 0 ,0
Exp/Cntr(USF)=0,0
Exp/Cntr=0.3,0.1

Type RM Length L Ch R = 1 ,37243   ,599.3,599.3,599.3
XS GIS Cut Line= 4
1694375.30852282411946.7013233771694445.32410187411974.953223696
1694671.33930442412075.677390049 1694813.8271495412183.771617355
#Sta/Elev= 30
       0 1136.83     5.2 1134.56    23.5 1121.01    52.6 1101.43    69.9  1093.2
    74.2 1089.49    82.9    1079    91.7 1063.73    96.1 1057.92   106.1 1050.18
   109.2 1048.91   113.6 1048.59   122.3 1048.76   129.31050.214   135.5 1051.41
   157.4  1052.7   196.8 1052.07   245.4 1052.96     306 1059.86   322.9 1063.21
   349.8 1063.42   352.7 1065.05   358.4 1070.56   361.2  1072.3   409.3  1099.2
   424.3 1111.73   443.5 1123.62   481.1 1138.76   495.4 1145.12   501.8 1149.05
#Mann= 6 ,-1,0
       0      .1       0   106.1    .045       0   129.3      .1       0
   165.5     .05       0   265.5     .06       0  402.94      .1       0
Bank Sta=106.1,129.3
XS Rating Curve= 0 ,0
Exp/Cntr(USF)=0,0
Exp/Cntr=0.3,0.1

Type RM Length L Ch R = 1 ,36644   ,365.7,365.7,365.7
XS GIS Cut Line= 3
1694079.53845739412122.2952450721694123.05793031412397.918573562
1694149.26955209412569.025962172
#Sta/Elev= 30
       0 1127.62    38.7 1103.51    42.8 1101.51      63 1094.61    75.2 1087.06
    79.2 1084.36    91.4 1070.61   107.6 1054.91   119.7 1046.84   123.8  1045.9
     140 1045.21   148.1 1045.53   153.41046.802   160.2 1048.54   180.5 1047.01
   192.6 1048.47   204.7 1048.62   220.9 1051.87   233.1 1052.96   265.5 1053.59
   289.8 1055.06   350.5 1055.61     377 1057.79     395 1057.81   403.1 1062.66
   419.1 1069.05   426.1 1071.11   431.4 1072.34   443.6 1071.35   452.1 1074.28
#Mann= 5 ,-1,0
       0      .1       0   119.7    .045       0   153.4      .1       0
     200     .05       0  299.04     .06       0
Bank Sta=119.7,153.4
XS Rating Curve= 0 ,0
Exp/Cntr(USF)=0,0
Exp/Cntr=0.3,0.1

Type RM Length L Ch R = 1 ,36278   ,527.3,527.3,527.3
XS GIS Cut Line= 3
1693690.48325779412226.3181278731693841.93801036412467.319121025
1693937.01179665412646.411602175
#Sta/Elev= 30
       0  1135.7    23.1 1120.91    46.3 1103.53    54.6  1099.2    66.6 1095.39
    70.7 1093.16    75.3 1088.78    82.9 1079.54    87.7 1072.22    92.7 1062.65
    97.1  1057.9   101.4 1054.58   110.1 1050.55   121.7  1049.3     129  1044.6
   130.9 1043.82     142 1043.51   153.4 1044.59   177.4  1047.3     191 1051.29
   196.3 1051.82   255.2 1051.19   390.2 1052.62   408.3 1056.15   421.9 1060.59
   430.9 1065.19   453.6  1065.4   458.1 1067.55   464.6 1072.14   487.4 1078.47
#Mann= 6 ,-1,0
       0      .1       0     129    .045       0   153.4      .1       0
     270     .05       0  344.64     .06       0  474.64      .1       0
Bank Sta=129,153.4
XS Rating Curve= 0 ,0
Exp/Cntr(USF)=0,0
Exp/Cntr=0.3,0.1