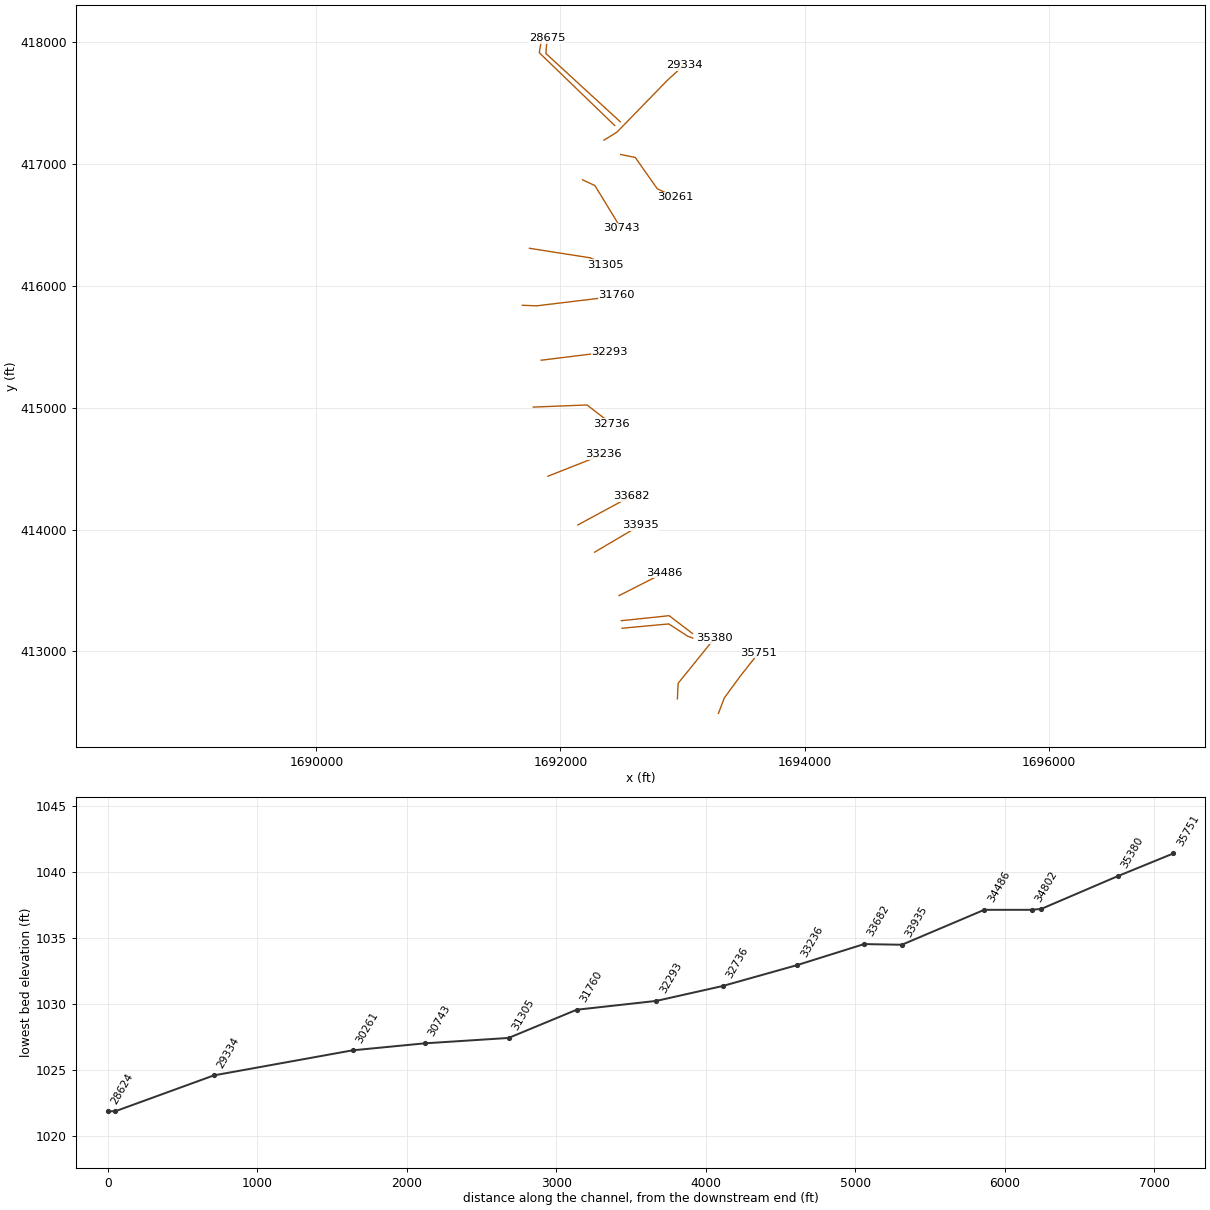
HEC-RAS study LNGDRN.prj: LNGDRN

--- LNGDRN.g01 (geometry) --- (continued)

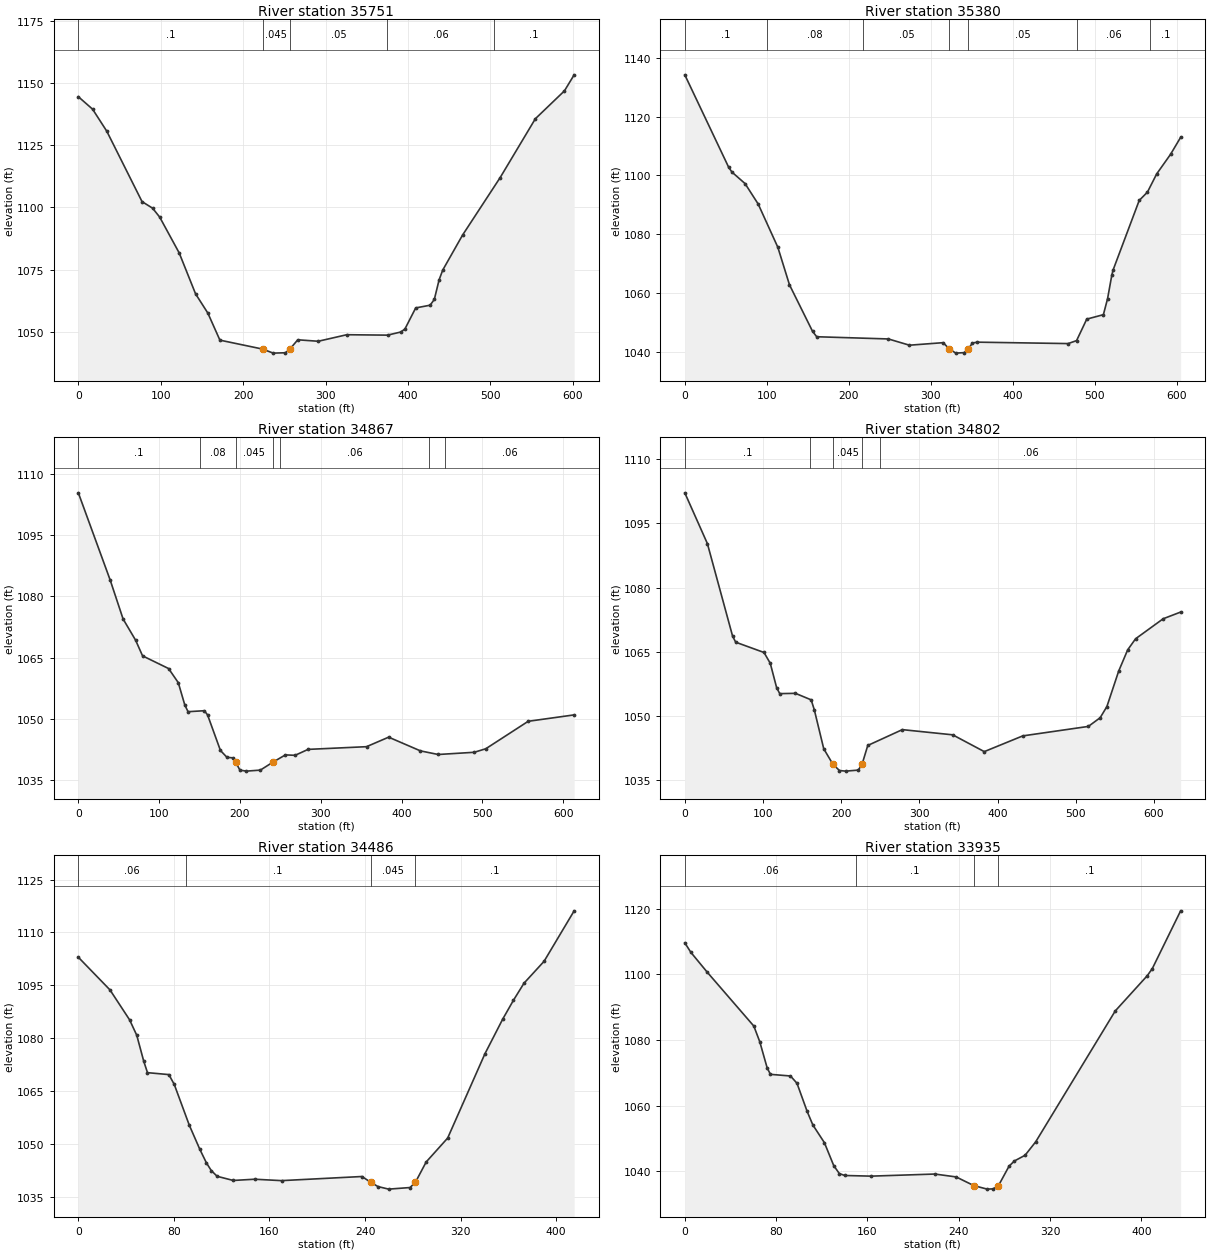
Type RM Length L Ch R = 1 ,35751   ,371.1,371.1,371.1
XS GIS Cut Line= 4
1693294.41279385412492.3255328731693342.93994416412619.709302425
1693471.84018715412795.6202222831693625.00400531412989.728823506
#Sta/Elev= 30
       0 1144.52    17.3 1139.51    34.5 1130.67    77.3 1102.35    90.1 1099.71
    98.7 1096.14   122.4 1081.72   142.3 1065.25   157.2 1057.52   171.8 1046.66
   223.6 1043.07   236.5 1041.44   251.4 1041.59   256.71043.054   266.3  1046.8
   291.1 1046.21   325.8 1048.84   375.2 1048.67   391.2 1049.92   396.3 1051.12
   409.4 1059.61   426.9 1060.71     432 1063.02   437.8 1070.89   442.2 1074.82
   466.3 1088.91   511.9 1112.01   554.6 1135.66   589.9 1146.87   601.7 1153.32
#Mann= 5 ,-1,0
       0      .1       0   223.6    .045       0   256.7     .05       0
   374.4     .06       0   504.4      .1       0
Bank Sta=223.6,256.7
XS Rating Curve= 0 ,0
Exp/Cntr(USF)=0,0
Exp/Cntr=0.3,0.1

Type RM Length L Ch R = 1 ,35380   ,512.7,512.7,512.7
XS GIS Cut Line= 3
1692957.97986459412611.1216020781692964.12158205412738.869325257
1693263.83739412413109.829059875
#Sta/Elev= 30
       0 1134.15    53.5 1102.79    57.5 1101.15    73.5 1097.25    89.5 1090.32
   113.5 1075.63   127.7 1062.89   155.8 1047.13   160.9 1045.28   248.3 1044.53
     274 1042.41   315.2 1043.27   322.5 1041.16   330.6 1039.72   340.9 1039.89
     346  1041.2   350.9 1043.16     357 1043.44   467.6 1042.96   477.9 1043.97
   490.3 1051.26   510.6 1052.77   515.7 1058.21   520.9 1066.23   522.5 1067.98
   554.3 1091.54   564.3 1094.34   575.6 1100.53   592.5 1107.17   604.8 1112.94
#Mann= 7 ,-1,0
       0      .1       0     100     .08       0   217.9     .05       0
   322.5    .045       0     346     .05       0   477.9     .06       0
   567.9      .1       0
Bank Sta=322.5,346
XS Rating Curve= 0 ,0
Exp/Cntr(USF)=0,0
Exp/Cntr=0.3,0.1

Type RM Length L Ch R = 1 ,34867   ,65.2,65.2,65.2
XS GIS Cut Line= 4
1692504.92118967413190.6109165341692887.42735311413225.987209106
 1693041.5103269413125.6751063511693084.34001617 413109.82812132
#Sta/Elev= 30
       0 1105.32    39.4 1083.99    55.4 1074.45    70.9 1069.26    79.5 1065.43
   111.7 1062.33   123.7 1058.88   131.8  1053.4   135.8 1051.77   155.9 1052.01
   159.9 1051.01   175.9 1042.28     184  1040.6     192 1040.47   194.81039.411
     200 1037.47   208.1 1037.23   225.3 1037.48   240.4 1039.37   256.3  1041.2
   268.3  1041.1   284.4 1042.55   356.7 1043.21   384.1 1045.54   423.5 1042.18
   445.4  1041.3     490 1041.84   504.3  1042.7   556.8 1049.42   613.7 1050.99
#Mann= 7 ,-1,0
       0      .1       0     150     .08       0   194.8    .045       0
   240.4     .08       0     250     .06       0  434.14     .05       0
  454.14     .06       0
Bank Sta=194.8,240.4
XS Rating Curve= 0 ,0
Exp/Cntr(USF)=0,0
Exp/Cntr=0.3,0.1

Type RM Length L Ch R = 1 ,34802   ,316.2,316.2,316.2
XS GIS Cut Line= 3
1692499.39364395413252.5194285361692890.74388053413293.423266823
1693081.86898857413147.236050643
#Sta/Elev= 30
       0 1102.09    28.9 1090.24    61.1 1068.67    65.1 1067.24   101.3 1064.84
   109.3 1062.32   117.4 1056.66   121.4 1055.24   141.5 1055.31   161.6 1053.79
   165.6 1051.49   177.7 1042.37   189.4 1038.77   197.8  1037.3   205.8 1037.16
   221.9  1037.4   226.8 1038.82     234 1043.15   278.2 1046.84   342.6 1045.63
     383 1041.71   432.2 1045.38   516.1 1047.59   531.2 1049.62   539.8 1052.22
   554.9 1060.51   566.4 1065.46   576.5 1068.04   611.8 1072.71   634.1 1074.27
#Mann= 5 ,-1,0
       0      .1       0     160     .08       0   189.4    .045       0
   226.8     .08       0     250     .06       0
Bank Sta=189.4,226.8
XS Rating Curve= 0 ,0
Exp/Cntr(USF)=0,0
Exp/Cntr=0.3,0.1

Type RM Length L Ch R = 1 ,34486   ,550.7,550.7,550.7
XS GIS Cut Line= 2
1692480.51074672413458.454073201 1692850.5302678413646.496780636
#Sta/Elev= 30
       0 1102.96    26.5 1093.69    42.9 1085.21    48.9 1080.83    54.8  1073.4
    57.9 1070.21    75.8 1069.66    80.3 1066.88    92.9  1055.3   101.7 1048.47
   107.2 1044.63   111.3 1042.43   116.2  1040.8   129.7 1039.62   147.6 1039.97
   170.1 1039.57   237.4 1040.74   244.61039.159   250.8 1037.89   259.8 1037.16
   277.7 1037.61   282.2  1039.1   291.2 1044.86   309.2 1051.65   340.4 1075.57
   355.3 1085.41   364.2 1090.71   373.1 1095.59   389.9  1101.8   415.1 1116.13
#Mann= 4 ,-1,0
       0     .06       0      90      .1       0   244.6    .045       0
   282.2      .1       0
Bank Sta=244.6,282.2
XS Rating Curve= 0 ,0
Exp/Cntr(USF)=0,0
Exp/Cntr=0.3,0.1

Type RM Length L Ch R = 1 ,33935   ,252.8,252.8,252.8
XS GIS Cut Line= 2
1692279.52536255413814.3093023771692653.48771459414035.411130957
#Sta/Elev= 30
       0 1109.62     5.3 1106.72    19.6 1100.68    60.5 1084.22    65.7 1079.43
    72.1 1071.55      75 1069.51    92.6 1069.01    98.3 1066.78   107.2  1058.2
   112.2 1054.07   122.3 1048.68   130.5 1041.67   135.4 1039.25   140.1 1038.67
   163.3 1038.47   219.1 1039.11   237.7 1038.23   253.2 1035.59   264.9 1034.51
   270.2 1034.59   274.8 1035.57   284.1 1041.52   288.8  1043.1   298.1 1044.83
   307.4 1048.92   377.1 1088.83   405.1 1099.56   409.6 1101.76   434.4 1119.37
#Mann= 4 ,-1,0
       0     .06       0     150      .1       0   253.2    .045       0
   274.8      .1       0
Bank Sta=253.2,274.8
XS Rating Curve= 0 ,0
Exp/Cntr(USF)=0,0
Exp/Cntr=0.3,0.1

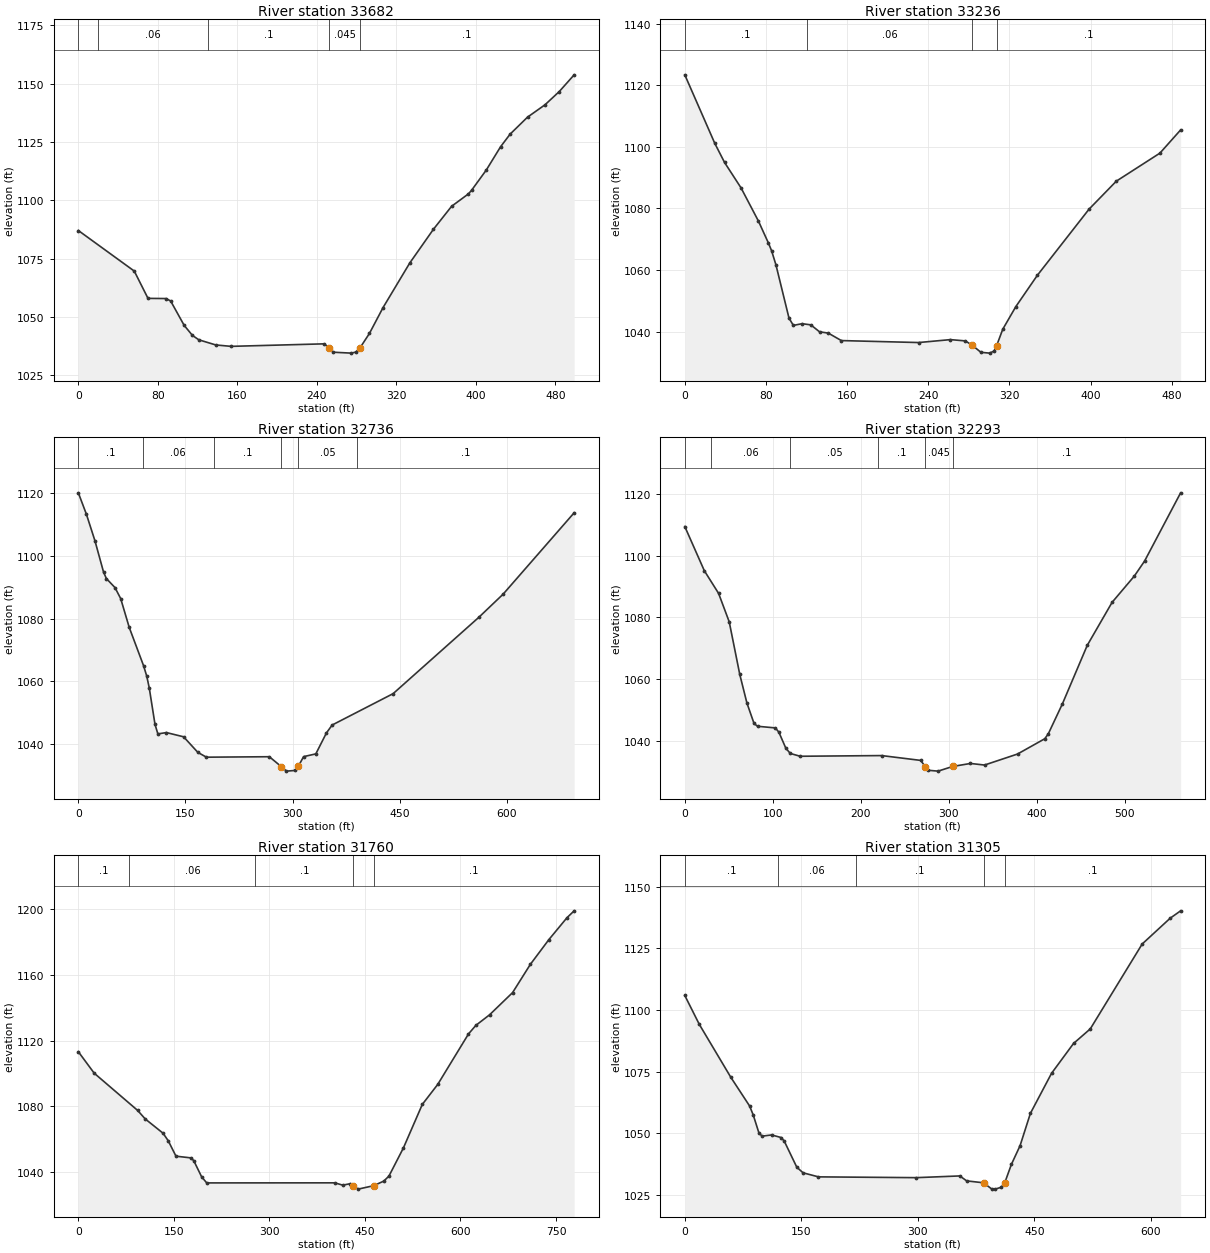
Type RM Length L Ch R = 1 ,33682   ,446.6,446.6,446.6
XS GIS Cut Line= 2
1692142.40537582414037.9868475851692581.32978917414275.130843421
#Sta/Elev= 30
       0 1087.09    56.3  1069.7    70.1 1058.01    88.3 1057.94    92.9  1056.9
   106.5 1046.44   114.8 1042.16   121.2 1040.27   138.3 1038.06   153.7 1037.46
   247.5 1038.54   252.61036.619   256.5 1034.95   274.7 1034.56   279.3 1035.02
   283.1 1036.61   292.9 1042.99   306.6 1054.07   333.5 1073.18   357.3 1087.62
   375.6 1097.47   392.5 1102.77   395.7 1104.33   410.5    1113   424.8 1122.93
   434.5 1128.39     452 1135.66   469.5 1140.92   483.9 1146.61   498.9 1153.78
#Mann= 5 ,-1,0
       0      .1       0      20     .06       0     130      .1       0
   252.6    .045       0   283.1      .1       0
Bank Sta=252.6,283.1
XS Rating Curve= 0 ,0
Exp/Cntr(USF)=0,0
Exp/Cntr=0.3,0.1

Type RM Length L Ch R = 1 ,33236   ,499.2,499.2,499.2
XS GIS Cut Line= 2
 1691896.6259471414437.0967670231692351.07420733414616.762358276
#Sta/Elev= 30
       0 1123.43    29.6 1101.13    39.2 1094.94    55.4  1086.7    72.6 1075.88
    82.4 1068.77    85.5 1066.29    89.8 1061.71   102.7 1044.35     107 1041.98
   115.6 1042.54   124.2 1042.16   132.8  1039.9   141.4 1039.48   154.3 1037.05
   230.4 1036.41   261.8 1037.36   276.6 1036.94   283.51035.464   291.9 1033.23
   300.5 1032.97   304.8 1033.65   307.4 1035.44   313.4 1040.74   326.3  1048.1
   347.5 1058.27   398.4 1079.75   425.3 1088.86   468.3 1097.98   488.7 1105.52
#Mann= 4 ,-1,0
       0      .1       0     120     .06       0   283.5    .045       0
   307.4      .1       0
Bank Sta=283.5,307.4
XS Rating Curve= 0 ,0
Exp/Cntr(USF)=0,0
Exp/Cntr=0.3,0.1

Type RM Length L Ch R = 1 ,32736   ,443.7,443.7,443.7
XS GIS Cut Line= 3
1691776.84888626415004.2763786261692217.20572757415021.890652278
1692418.00844721414866.885044138
#Sta/Elev= 30
       0 1120.04    11.3 1113.22    23.3 1104.74    35.3  1094.8    39.3 1092.72
    51.3 1089.86    59.3 1086.36    71.3 1077.15    91.3    1065    95.8 1061.65
    99.3 1057.93   107.4 1046.24   111.4 1043.24   123.4 1043.66   147.4 1042.32
   167.4 1037.35   179.4 1035.82   267.5 1035.97   284.4 1032.79   291.5 1031.38
   303.5 1031.59     3081032.889   315.5    1036   332.6 1036.87   347.5 1043.56
   355.5 1046.07   440.9 1056.07   560.8 1080.36   594.9 1087.75   694.4 1113.69
#Mann= 6 ,-1,0
       0      .1       0      90     .06       0     190      .1       0
   284.4    .045       0     308     .05       0     390      .1       0
Bank Sta=284.4,308
XS Rating Curve= 0 ,0
Exp/Cntr(USF)=0,0
Exp/Cntr=0.3,0.1

Type RM Length L Ch R = 1 ,32293   ,532.5,532.5,532.5
XS GIS Cut Line= 2
1691842.04359562415388.7823752341692401.38908287415458.122724894
#Sta/Elev= 30
       0 1109.38    22.2 1095.08    38.4 1087.76    50.5 1078.54    62.5 1061.51
    70.6 1052.29    78.7 1045.67    82.7 1044.76   102.9 1044.23   106.9 1042.87
   114.9 1037.63     120 1035.96   131.1 1035.06   223.8 1035.28   268.1 1033.72
   273.41031.704   276.2 1030.53   287.9 1030.25   304.4 1031.75   324.7 1032.73
   340.7 1032.22   378.2 1035.78   409.2 1040.73   413.2 1042.32   429.3 1052.06
   457.5 1070.96   485.7 1084.85   510.9 1093.32   522.6 1098.19   563.6 1120.28
#Mann= 6 ,-1,0
       0      .1       0      30     .06       0     120     .05       0
     220      .1       0   273.4    .045       0   304.4      .1       0
Bank Sta=273.4,304.4
XS Rating Curve= 0 ,0
Exp/Cntr(USF)=0,0
Exp/Cntr=0.3,0.1

Type RM Length L Ch R = 1 ,31760   ,455.3,455.3,455.3
XS GIS Cut Line= 4
1691687.18348138415839.494648021 1691805.0620758415834.871958043
1692302.00124836415894.9669277481692459.17270759415925.014412601
#Sta/Elev= 30
       0 1113.23    24.9 1100.16      93 1077.53     105 1072.32     133 1063.62
   141.2    1059   153.3 1049.64   177.5 1048.56   181.5 1046.69   193.6 1037.05
   201.6 1033.37   402.6 1033.41   415.2    1032   427.3 1032.91   431.7 1031.62
   439.3 1029.58   463.7 1031.68   479.6 1034.47   487.7 1037.53   510.4 1054.65
   540.1 1081.16   564.3 1093.32   612.6 1124.05   624.2 1129.28   645.6 1135.66
   681.8  1149.2   709.8 1166.45   738.8 1181.47   767.3 1194.83   778.5 1198.99
#Mann= 5 ,-1,0
       0      .1       0      80     .06       0  277.97      .1       0
   431.7    .045       0   463.7      .1       0
Bank Sta=431.7,463.7
XS Rating Curve= 0 ,0
Exp/Cntr(USF)=0,0
Exp/Cntr=0.3,0.1

Type RM Length L Ch R = 1 ,31305   ,561.7,561.7,561.7
XS GIS Cut Line= 3
1691745.64996647416306.8640211291692245.52454717416228.232064615
1692365.34467138416172.066381391
#Sta/Elev= 30
       0 1105.94    18.7 1094.21    59.2  1072.8    83.5 1061.11    88.2 1057.41
    95.6 1050.05    99.7 1048.93   111.8  1049.4     124 1048.36     128 1046.94
   144.2 1036.33   152.3 1034.05   172.1 1032.41   298.1 1032.09   354.1 1032.79
   362.9 1030.78   384.6 1030.01   395.3 1027.47   399.6 1027.44   407.4  1028.2
   411.71029.783   420.5 1037.46   431.7 1045.07     445 1058.17   472.2 1074.38
   500.5 1086.48   522.1  1092.4   588.9  1126.8     625 1137.27   638.4 1140.25
#Mann= 5 ,-1,0
       0      .1       0     120     .06       0     220      .1       0
   384.6    .045       0   411.7      .1       0
Bank Sta=384.6,411.7
XS Rating Curve= 0 ,0
Exp/Cntr(USF)=0,0
Exp/Cntr=0.3,0.1

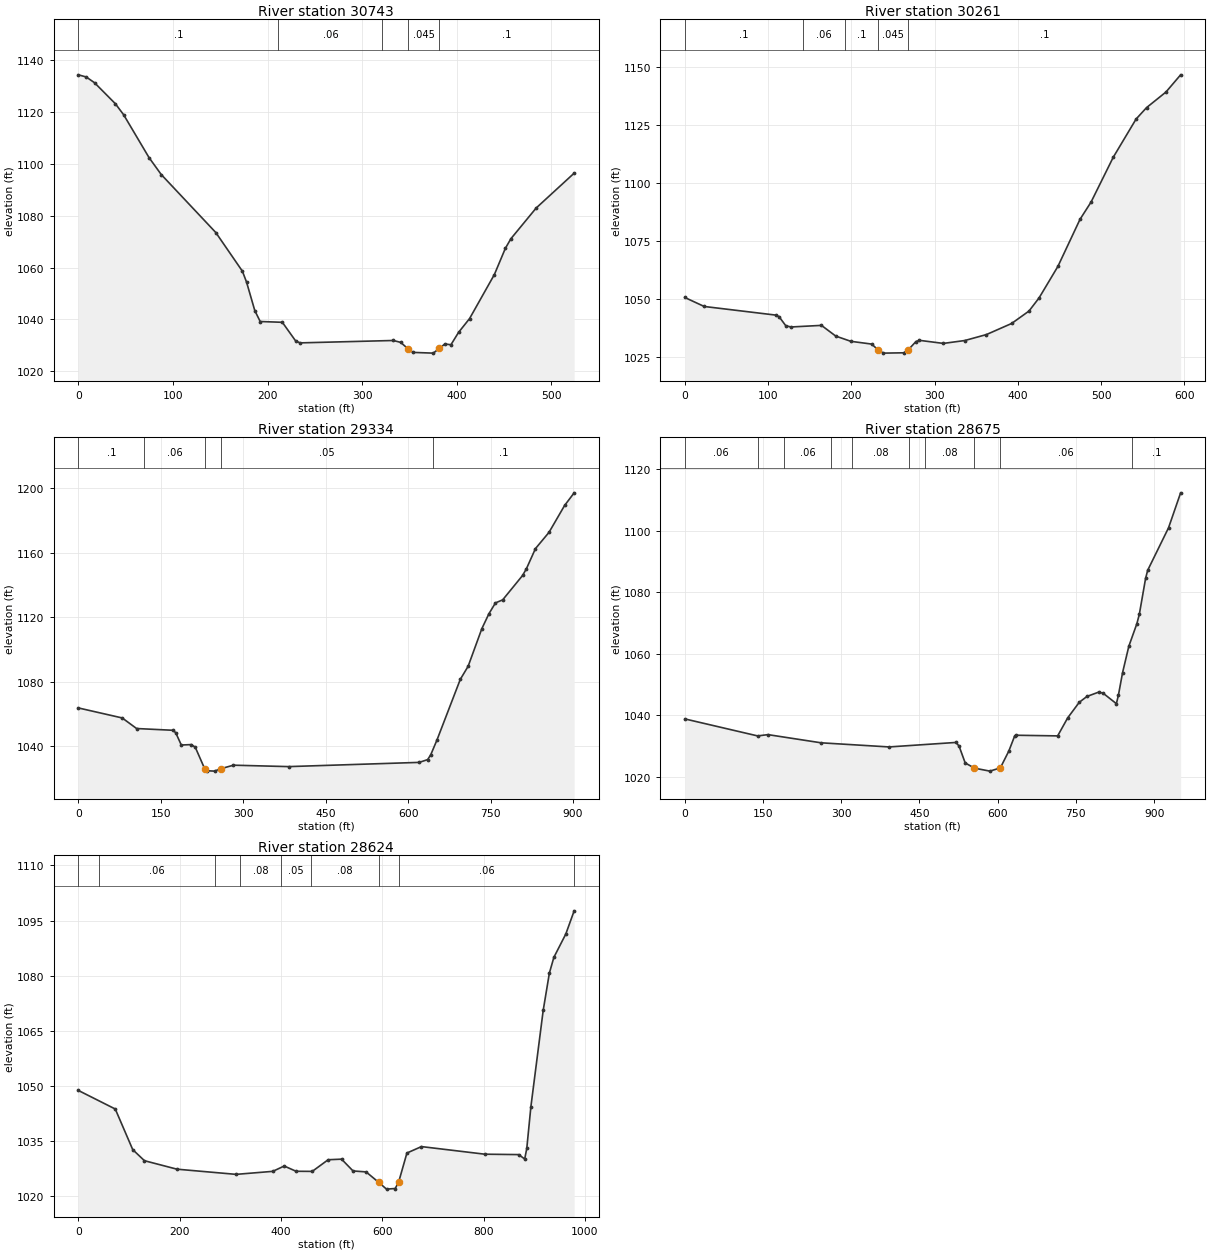
Type RM Length L Ch R = 1 ,30743   ,481.8,481.8,481.8
XS GIS Cut Line= 3
1692180.62563309416868.2601237611692281.72386289416821.455387741
1692497.02564858416469.483772869
#Sta/Elev= 30
       0 1134.26     8.3 1133.44    17.1 1131.22    39.1 1123.14    47.9 1118.87
    74.7 1102.38    87.6 1095.85   145.3 1073.49   173.4 1058.59   177.8 1054.37
   186.5 1043.41   192.2 1039.21   215.6 1038.91   229.7 1031.71   234.4 1030.98
   332.9  1031.9   340.7 1031.17   348.21028.761   353.6 1027.31   375.1 1027.03
   381.5 1028.84   387.3 1030.54   393.8 1030.27   401.8    1035   413.5 1040.36
   439.7 1057.32   451.3 1067.41   457.1 1071.09   483.9 1082.96     524 1096.37
#Mann= 5 ,-1,0
       0      .1       0  211.41     .06       0  321.41      .1       0
   348.2    .045       0   381.5      .1       0
Bank Sta=348.2,381.5
XS Rating Curve= 0 ,0
Exp/Cntr(USF)=0,0
Exp/Cntr=0.3,0.1

Type RM Length L Ch R = 1 ,30261   ,927.2,927.2,927.2
XS GIS Cut Line= 4
 1692493.2812697 417076.073151691692613.10139391 417051.73468896
1692792.83158023 416795.244735571692936.99016717 416725.97372626
#Sta/Elev= 30
       0 1050.48    23.3 1046.61     109  1042.9   113.1 1042.26   121.3 1038.29
   127.5 1037.77   164.1 1038.46   181.3 1033.84   199.4 1031.59   224.4  1030.4
   232.1  1027.9   238.5  1026.5   262.9 1026.64   268.11027.859   277.6 1031.49
   281.8 1032.01   310.5 1030.69   336.2 1031.93   362.2  1034.5   392.4 1039.27
   413.3 1044.63   425.4 1050.29     448 1063.86   474.6 1084.18   487.9 1091.64
   514.5 1110.93   541.9 1127.38   554.5 1132.32   577.8 1139.04   595.4 1146.45
#Mann= 5 ,-1,0
       0      .1       0  142.27     .06       0  192.27      .1       0
   232.1    .045       0   268.1      .1       0
Bank Sta=232.1,268.1
XS Rating Curve= 0 ,0
Exp/Cntr(USF)=0,0
Exp/Cntr=0.3,0.1

Type RM Length L Ch R = 1 ,29334   ,658.9,658.9,658.9
XS GIS Cut Line= 4
1692356.74132352417194.0309059881692462.89446481 417259.74475536
 1692879.0821775417687.7272615291693012.19484674417809.045137293
#Sta/Elev= 30
       0 1063.78    79.8 1057.57     106 1051.01   172.5 1049.92   177.2 1048.36
   187.3 1040.79   205.5 1041.05   212.7 1039.42   229.9 1026.01   233.8 1024.84
   247.9  1024.6   259.2 1026.11   282.2 1028.28   382.6  1027.4     620 1030.02
   635.4 1031.74   641.1 1034.79   652.4 1043.93   694.8  1081.5     709 1089.57
     734 1112.94   746.8 1122.13   758.7 1128.88   771.9 1130.79   808.1 1145.91
   815.2 1150.18   831.5 1162.56   856.2 1172.66   884.5 1189.29   901.9 1197.14
#Mann= 5 ,-1,0
       0      .1       0     120     .06       0   229.9    .045       0
   259.2     .05       0  644.85      .1       0
Bank Sta=229.9,259.2
XS Rating Curve= 0 ,0
Exp/Cntr(USF)=0,0
Exp/Cntr=0.3,0.1

Type RM Length L Ch R = 1 ,28675   ,51.5,51.5,51.5
XS GIS Cut Line= 3
1692489.56483076417344.5931050991691880.30645868417904.717737499
1691890.13320661418027.552086709
#Sta/Elev= 30
       0 1038.85   139.7 1033.32   159.5 1033.74   261.4 1031.08   391.7 1029.74
     520  1031.2   525.9 1030.03   537.7 1024.54   555.5 1022.85     585 1021.88
   605.1 1022.93   621.4 1028.42   632.3 1033.19   635.1 1033.54     715 1033.33
   734.2 1039.17   756.4 1044.24     771 1046.13   793.6 1047.55   802.1 1047.21
   827.6  1043.8   831.4 1046.46   839.5  1053.9   851.5 1062.47   866.9 1069.79
   871.6 1072.83   883.6 1084.48   887.6 1087.13   927.6 1100.94   950.8 1112.31
#Mann= 10 ,-1,0
       0     .06       0     140     .05       0     190     .06       0
     280     .05       0     320     .08       0     430     .06       0
     460     .08       0   555.5    .045       0   605.1     .06       0
  857.61      .1       0
Bank Sta=555.5,605.1
XS Rating Curve= 0 ,0
Exp/Cntr(USF)=0,0
Exp/Cntr=0.3,0.1

Type RM Length L Ch R = 1 ,28624   ,639.1,639.1,639.1
XS GIS Cut Line= 3
1692444.11612155417313.8845177971691826.25934502417910.859454959
 1691845.9128409418028.780430201
#Sta/Elev= 30
       0 1048.75    72.9 1043.69   107.4 1032.63   130.5 1029.62   194.7 1027.31
   311.5  1025.9   383.8 1026.72   406.4 1028.17   429.8 1026.74   461.7 1026.71
   493.1 1029.88   519.6 1030.04   542.2 1026.83     568 1026.57   593.1  1023.7
   608.3 1021.88   625.5 1022.05   632.31023.816   648.6 1031.71   677.3 1033.46
   802.4 1031.39   869.2 1031.28   881.1 1030.08   885.2 1032.97   893.3 1044.33
   917.6 1070.55   929.8 1080.71   938.7    1085   962.2 1091.33   978.7 1097.65
#Mann= 9 ,-1,0
       0      .1       0      40     .06       0     270     .05       0
     320     .08       0     400     .05       0     460     .08       0
   593.1    .045       0   632.3     .06       0  978.69      .1       0
Bank Sta=593.1,632.3
XS Rating Curve= 0 ,0
Exp/Cntr(USF)=0,0
Exp/Cntr=0.3,0.1