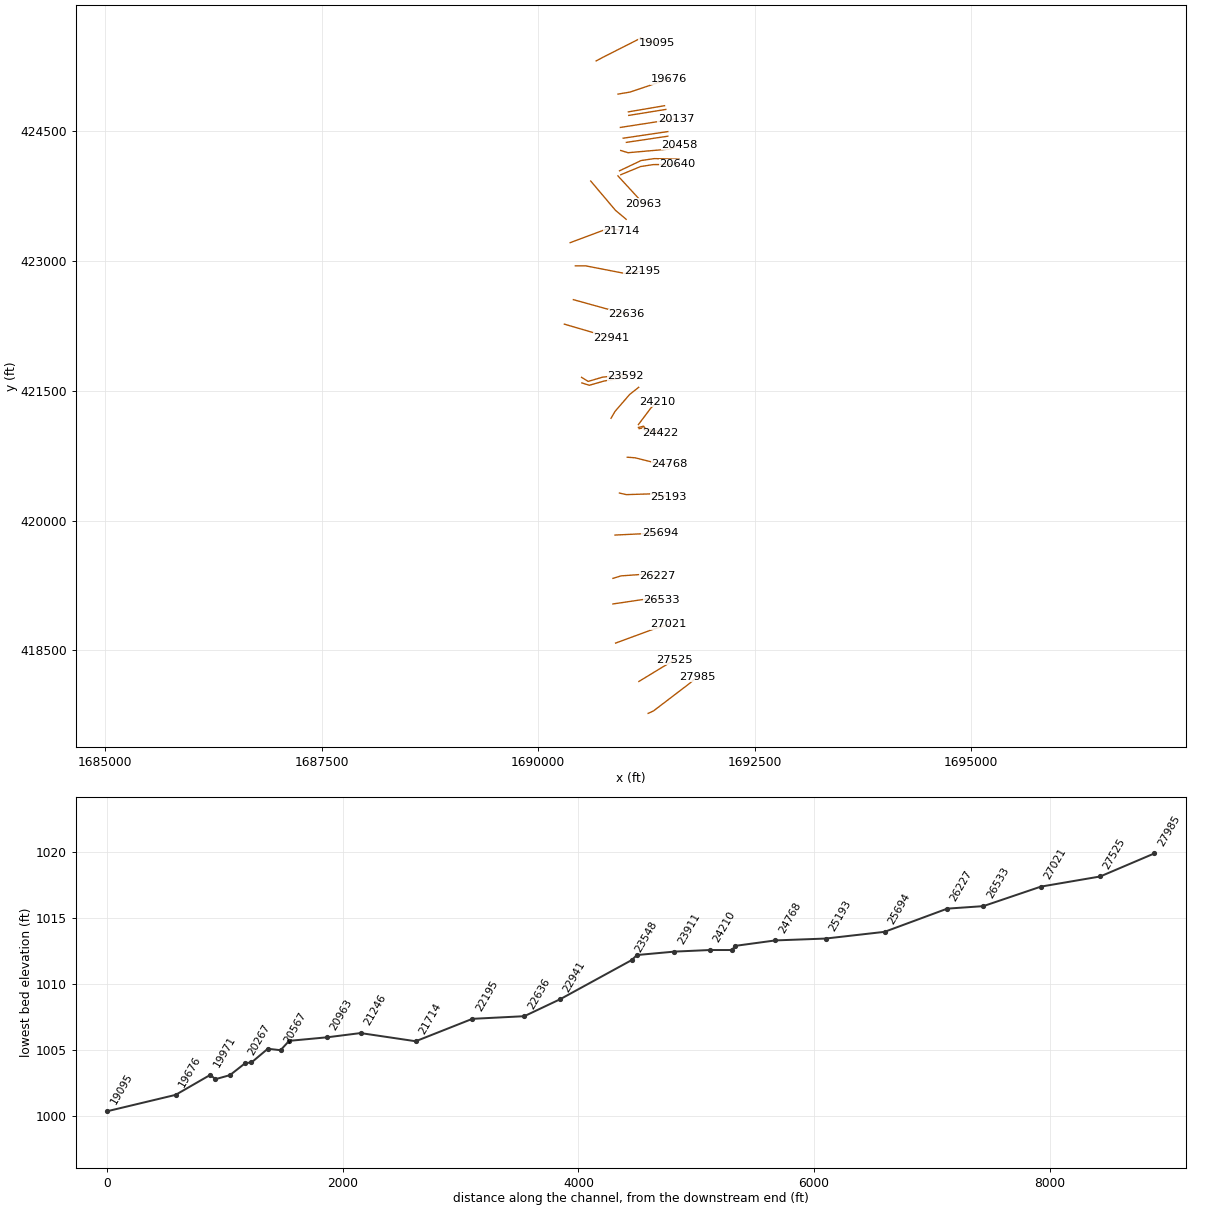
HEC-RAS study LNGDRN.prj: LNGDRN

--- LNGDRN.g01 (geometry) --- (continued)

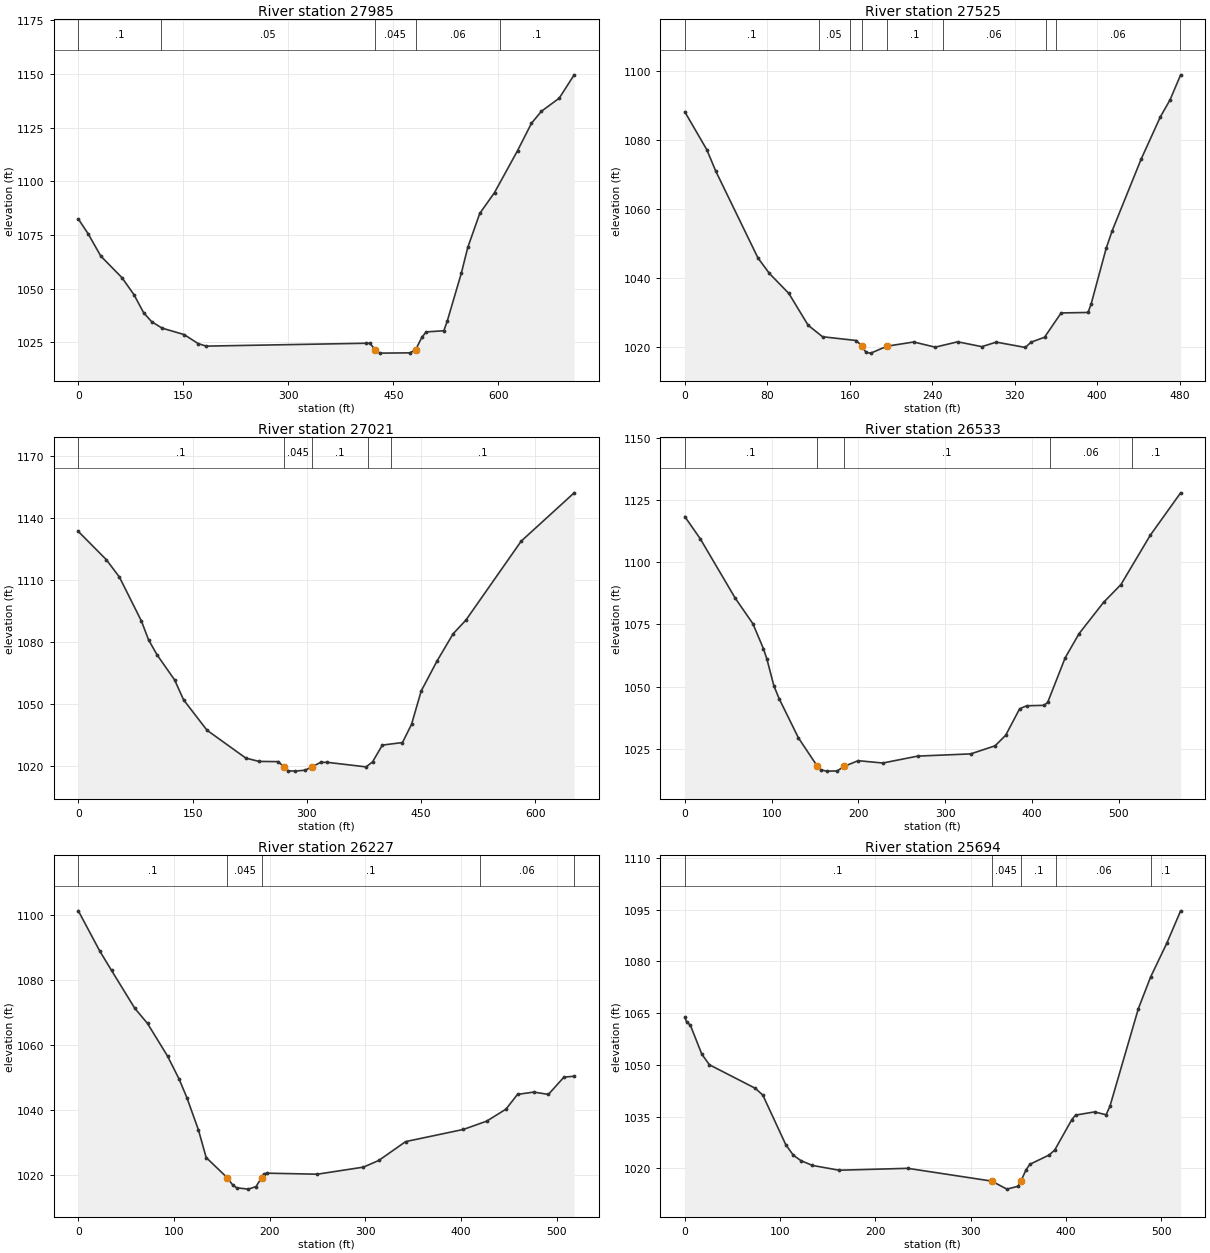
Type RM Length L Ch R = 1 ,27985   ,460,460,460
XS GIS Cut Line= 4
1691269.07039647417773.0120964391691330.85264802417801.094938051
1691748.35089332418119.3671429881691836.34379704 418194.25472062
#Sta/Elev= 30
       0 1082.45      14 1075.56    32.1 1065.15    62.4 1055.07    79.5 1047.15
    93.3 1038.74   104.7 1034.58   119.7 1031.56   151.1 1028.57   171.1 1024.37
   182.5 1023.18   411.5 1024.52   416.6 1024.47   424.11021.521   430.8 1019.91
   473.6 1020.04   481.9  1021.5   490.8 1027.28     497  1029.8   522.2 1030.34
   527.2 1034.97   547.3 1057.29   556.4 1069.17   573.5 1085.02   594.6 1094.74
   627.6 1114.35   647.4 1127.05   661.6 1132.65   687.1 1138.76   708.4 1149.64
#Mann= 5 ,-1,0
       0      .1       0  117.87     .05       0   424.1    .045       0
   481.9     .06       0  602.84      .1       0
Bank Sta=424.1,481.9
XS Rating Curve= 0 ,0
Exp/Cntr(USF)=0,0
Exp/Cntr=0.3,0.1

Type RM Length L Ch R = 1 ,27525   ,503.6,503.6,503.6
XS GIS Cut Line= 2
1691161.92339699418141.2079756791691572.84114541 418390.94249106
#Sta/Elev= 30
       0 1088.24    21.3 1077.26    30.2 1070.91      71 1045.78    82.1 1041.29
   100.9  1035.5   119.6 1026.27   133.6 1022.92   166.4 1021.82   171.91020.151
   175.8 1018.35   180.4 1018.16   196.2 1020.18   222.1  1021.4   242.8 1019.89
   264.7 1021.45   288.1 1020.04   302.1 1021.36   330.2 1019.81   335.9 1021.35
   348.9 1022.77     365 1029.83   391.1 1029.97   394.1 1032.43   408.7  1048.6
   414.5 1053.69   442.6  1074.5   461.3 1086.81   470.6 1091.69   480.9 1098.98
#Mann= 9 ,-1,0
       0      .1       0     130     .05       0     160      .1       0
   171.9    .045       0   196.2      .1       0     250     .06       0
     350      .1       0     360     .06       0     480      .1       0
Bank Sta=171.9,196.2
XS Rating Curve= 0 ,0
Exp/Cntr(USF)=0,0
Exp/Cntr=0.3,0.1

Type RM Length L Ch R = 1 ,27021   ,488.5,488.5,488.5
XS GIS Cut Line= 3
1690893.57074581418584.8408454091691311.06899111418738.360379555
 1691507.6488824418800.142631102
#Sta/Elev= 30
       0 1133.36    36.8 1119.68    53.9  1111.3    82.8 1090.02    92.2 1080.91
   103.4 1073.63   126.4 1061.52   138.2 1051.87   168.9 1037.18   219.9  1023.7
   237.1 1022.09   262.7 1021.98   269.7 1019.44   275.5 1017.58     284 1017.39
   297.8 1017.84   307.1 1019.54   318.1 1021.64   326.6 1021.66   377.8 1019.44
   386.3  1021.9   399.1 1029.99   425.5 1031.22   437.4 1040.01   450.1 1056.16
   471.1 1070.82   492.1 1083.88   508.8 1090.46   581.4 1128.68   650.9 1152.04
#Mann= 5 ,-1,0
       0      .1       0   269.7    .045       0   307.1      .1       0
     380     .06       0     410      .1       0
Bank Sta=269.7,307.1
XS Rating Curve= 0 ,0
Exp/Cntr(USF)=0,0
Exp/Cntr=0.3,0.1

Type RM Length L Ch R = 1 ,26533   ,306.1,306.1,306.1
XS GIS Cut Line= 3
1690862.59969427419036.6786779711691282.69316858419098.587189974
1691428.62037544419087.532098544
#Sta/Elev= 30
       0 1118.47    17.7 1109.58    58.1 1085.59    78.4 1075.31    90.5 1065.29
    94.5 1061.14   102.6 1050.26   108.8 1044.99   130.9 1029.28   152.7 1017.85
   156.3 1016.45   163.3 1015.91   175.4 1015.98   183.5 1017.82   199.6 1020.12
     228 1019.18   268.4 1021.97   329.2 1022.85   357.3 1026.11   369.5 1030.34
   385.6 1041.03   393.7 1042.24   413.9 1042.42     418 1043.71   438.1  1061.6
   454.1 1071.33   482.2 1083.88   502.3 1091.09     536 1110.92     571 1128.03
#Mann= 5 ,-1,0
       0      .1       0   152.7    .045       0   183.5      .1       0
     420     .06       0  514.63      .1       0
Bank Sta=152.7,183.5
XS Rating Curve= 0 ,0
Exp/Cntr(USF)=0,0
Exp/Cntr=0.3,0.1

Type RM Length L Ch R = 1 ,26227   ,532.3,532.3,532.3
XS GIS Cut Line= 4
1690862.90665961419332.2521278361690957.07966067419360.913475986
1691227.31522894419380.0210414191691374.71644799419359.548649883
#Sta/Elev= 30
       0 1101.43    22.2 1089.15    34.7 1083.07    58.9 1071.46    72.3 1066.74
    93.2 1056.71   105.5 1049.51   113.5 1043.85   125.5 1033.98   133.6 1025.46
   155.6 1019.24   161.6  1016.9   165.6 1016.12   177.7 1015.72   185.7 1016.51
   191.61019.269   193.7 1020.38   197.7 1020.63   249.8 1020.32     298  1022.5
     314 1024.55   342.1 1030.36   402.5 1034.11   426.7 1036.65   446.9 1040.34
     459  1044.9     476 1045.61   491.3 1044.89   507.5 1050.21   518.2 1050.49
#Mann= 5 ,-1,0
       0      .1       0   155.6    .045       0   191.6      .1       0
  419.35     .06       0  518.16     .12       0
Bank Sta=155.6,191.6
XS Rating Curve= 0 ,0
Exp/Cntr(USF)=0,0
Exp/Cntr=0.3,0.1

Type RM Length L Ch R = 1 ,25694   ,501.2,501.2,501.2
XS GIS Cut Line= 2
1690886.26458046419832.1979904111691406.26332545419856.764860254
#Sta/Elev= 30
       0 1063.73     1.9 1062.46     5.9 1061.43    17.9 1053.05    25.9    1050
    73.9  1043.2    81.9 1041.22     106 1026.86     114 1023.77     122 1022.21
     134 1020.83     162 1019.44   234.1 1019.99   322.2 1016.29   338.2 1013.96
   350.1  1014.8   353.11016.415   358.2 1019.51   362.3 1021.15   382.3 1023.82
   388.3 1025.24   406.3 1034.08   410.3 1035.42   430.3 1036.34   442.3 1035.51
   446.3 1037.91   476.2 1066.25   489.1 1075.45     506 1085.18   520.6 1094.62
#Mann= 5 ,-1,0
       0      .1       0   322.2    .045       0   353.1      .1       0
     390     .06       0     490      .1       0
Bank Sta=322.2,353.1
XS Rating Curve= 0 ,0
Exp/Cntr(USF)=0,0
Exp/Cntr=0.3,0.1

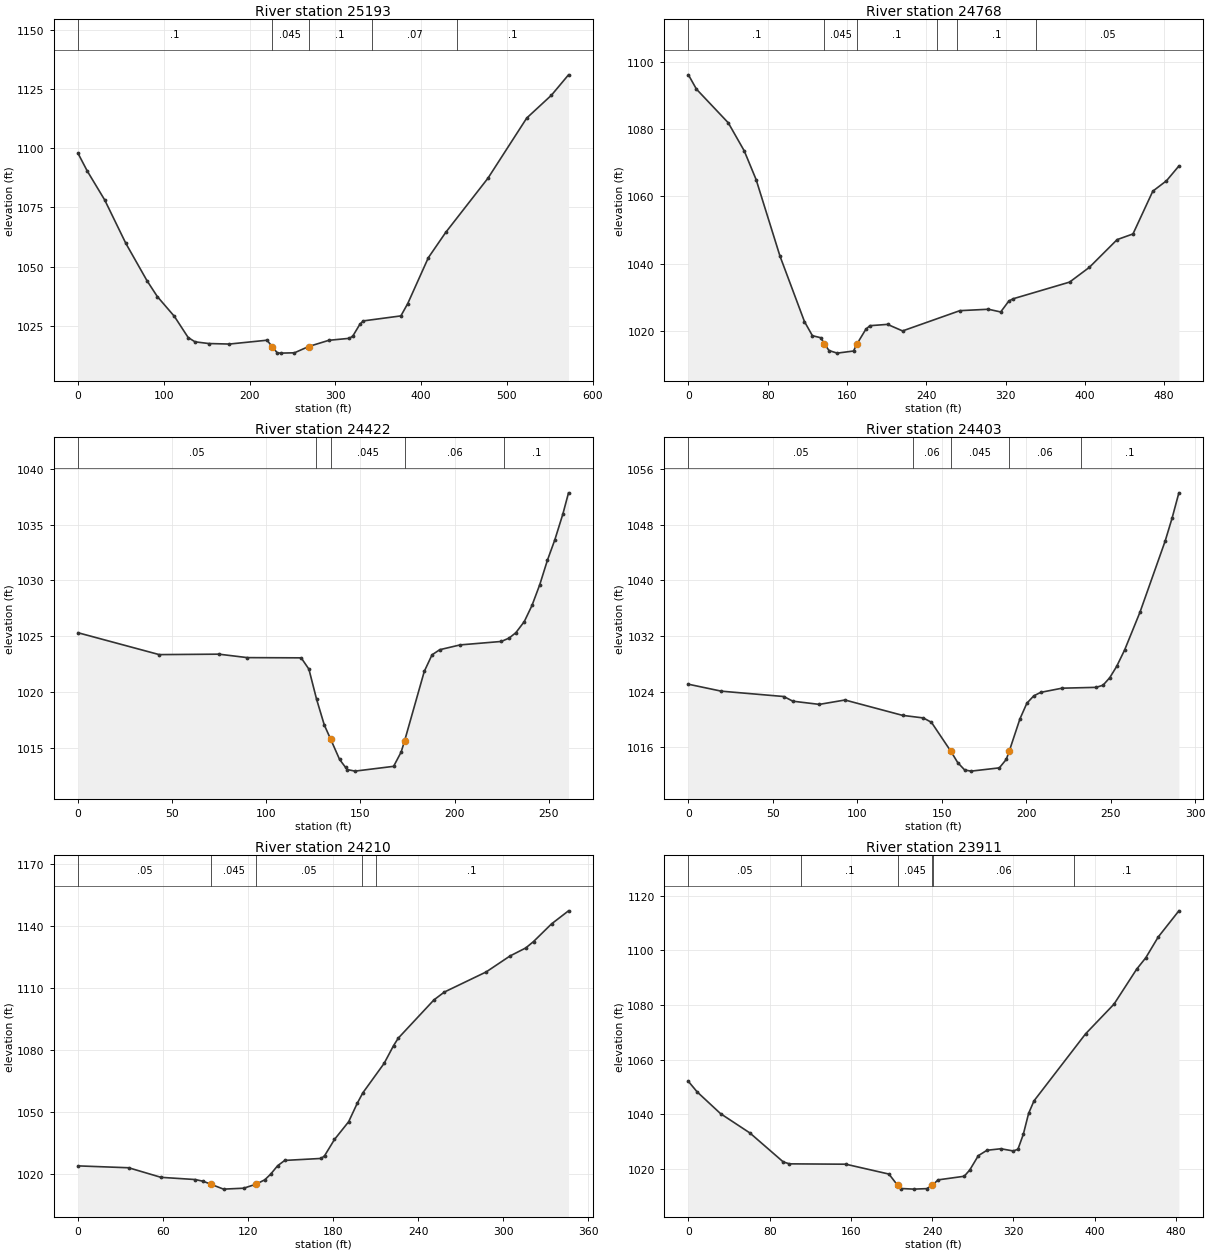
Type RM Length L Ch R = 1 ,25193   ,425.1,425.1,425.1
XS GIS Cut Line= 4
1690937.79051598420317.3079535671691018.16360867420299.110272202
1691357.85366081420309.7255863321691503.43511173 420274.84669705
#Sta/Elev= 30
       0 1097.73    10.6 1090.37    31.1 1078.06    55.7 1059.78    80.3 1044.07
    92.4 1037.34   112.4 1028.93   128.4 1020.04   136.4 1018.22   152.4  1017.5
   176.4 1017.28   220.4  1018.9   226.3 1016.22   232.4 1013.54   236.4 1013.45
   252.4 1013.59   268.8 1016.22   292.5 1018.86   316.5  1019.7   320.5  1020.7
   328.5 1025.53   332.5 1027.04   376.5 1029.16   384.5 1034.37   408.5 1053.71
   428.7 1064.35   478.1 1087.29   523.3 1112.66   552.1 1122.29     572 1130.88
#Mann= 5 ,-1,0
       0      .1       0   226.3    .045       0   268.8      .1       0
  342.41     .07       0  442.26      .1       0
Bank Sta=226.3,268.8
XS Rating Curve= 0 ,0
Exp/Cntr(USF)=0,0
Exp/Cntr=0.3,0.1

Type RM Length L Ch R = 1 ,24768   ,346,346,346
XS GIS Cut Line= 4
1691028.00686448420731.252063656 1691118.6586142420724.619008799
1691382.87529935420658.2884602251691514.43088736420653.866423653
#Sta/Elev= 30
       0 1096.27     8.1    1092    40.2 1081.97    56.3 1073.62    68.3 1065.05
    92.4 1042.22   117.1 1022.71   125.1 1018.51   133.6 1017.89   137.11016.102
   141.9 1014.08   150.1 1013.31   166.6 1013.94   169.9 1015.97     179 1020.41
   183.1 1021.49   200.9 1021.88   216.1 1019.93   273.9 1025.97   302.7 1026.39
   315.1 1025.58   323.3 1028.83   327.5  1029.5   384.6 1034.48   404.6 1038.89
   432.6 1047.15   448.6 1048.84   468.6 1061.59   482.4 1064.69   494.9 1069.09
#Mann= 6 ,-1,0
       0      .1       0   137.1    .045       0   169.9      .1       0
  250.89     .06       0  270.89      .1       0  350.89     .05       0
Bank Sta=137.1,169.9
XS Rating Curve= 0 ,0
Exp/Cntr(USF)=0,0
Exp/Cntr=0.3,0.1

Type RM Length L Ch R = 1 ,24422   ,19.4,19.4,19.4
XS GIS Cut Line= 4
1691165.62776039421061.4258820721691208.05924649421069.259387197
1691230.90696977421045.1060797271691411.07758766421007.244138288
#Sta/Elev= 30
       0  1025.3    43.1 1023.34    74.8 1023.38    89.9 1023.07   118.5 1023.05
   122.6 1022.04   126.7 1019.33   130.8 1017.02   134.1 1015.78   138.9 1013.94
   142.1 1013.22     143 1013.03   147.1 1012.89   167.6 1013.32   171.6  1014.6
   173.41015.588   183.9 1021.84     188 1023.32   192.1 1023.78   202.9 1024.21
   224.8 1024.52   228.9 1024.82   232.5  1025.3     237  1026.3   241.1 1027.75
   245.2  1029.6   249.3 1031.81   253.2 1033.62   257.5 1035.95   260.5 1037.85
#Mann= 5 ,-1,0
       0     .05       0   126.4     .06       0   134.1    .045       0
   173.4     .06       0   226.4      .1       0
Bank Sta=134.1,173.4
XS Rating Curve= 0 ,0
Exp/Cntr(USF)=0,0
Exp/Cntr=0.3,0.1

Type RM Length L Ch R = 1 ,24403   ,192.7,192.7,192.7
XS GIS Cut Line= 4
1691157.14146317421075.134516041 1691217.1983358421089.495942105
1691234.82372234421064.037050447 1691428.0501821421022.258356445
#Sta/Elev= 30
       0 1025.08    19.5 1024.08    56.5 1023.31    61.8 1022.64    77.5 1022.18
    92.7 1022.81   126.8  1020.6   139.1 1020.23   143.9  1019.6   155.4 1015.43
   159.5 1013.79   163.6 1012.74   167.4 1012.58   184.1 1013.05   188.2 1014.27
   189.9 1015.41   196.3  1020.1   200.4 1022.35   204.5 1023.41   208.6 1023.91
   221.2 1024.51   241.4 1024.63   245.5 1024.94   249.5 1026.03   253.6 1027.66
   258.3 1030.02   267.4 1035.46   282.3 1045.69   286.4 1048.99   290.4 1052.61
#Mann= 5 ,-1,0
       0     .05       0  132.71     .06       0   155.4    .045       0
   189.9     .06       0  232.71      .1       0
Bank Sta=155.4,189.9
XS Rating Curve= 0 ,0
Exp/Cntr(USF)=0,0
Exp/Cntr=0.3,0.1

Type RM Length L Ch R = 1 ,24210   ,299,299,299
XS GIS Cut Line= 3
1691156.96761477421107.9795533831691301.63918162421300.420033814
1691378.06944335421372.755817239
#Sta/Elev= 30
       0 1023.83    35.7 1022.92    58.5 1018.29    82.6 1017.22    88.3 1016.38
    94.1 1014.84   102.6 1012.58   116.9 1013.03   125.5 1014.97   131.7 1017.08
   135.8 1019.77   140.8 1023.91   145.8 1026.47   171.7 1027.44     174 1028.84
   180.9 1036.62   190.9 1045.21   196.9 1054.04   200.9 1059.18   215.9 1073.42
   222.6 1082.06   225.9 1085.65   251.1 1104.18   258.4 1107.95   287.9 1117.68
   304.7  1125.4   315.8 1129.28   321.3 1132.38     334 1140.93     346 1147.26
#Mann= 5 ,-1,0
       0     .05       0    94.1    .045       0   125.5     .05       0
     200     .06       0     210      .1       0
Bank Sta=94.1,125.5
XS Rating Curve= 0 ,0
Exp/Cntr(USF)=0,0
Exp/Cntr=0.3,0.1

Type RM Length L Ch R = 1 ,23911   ,318.8,318.8,318.8
XS GIS Cut Line= 4
1690840.74509116421181.1396961421690886.51316967421259.741396202
1691055.65606854421455.7481672391691160.12668254421538.329700214
#Sta/Elev= 30
       0 1051.97     8.6 1048.12    31.7 1040.13    60.5 1033.07    93.4 1022.44
    99.5 1021.73     155  1021.6   197.5 1017.98   206.1 1013.82   209.7 1012.68
     222 1012.46   234.7 1012.64   240.1 1013.83   245.8 1015.85   271.6 1017.18
     277 1019.45   285.5 1024.73     294 1026.71   307.7 1027.27   319.9 1026.46
   324.5 1027.08   329.8 1032.56     335 1040.22   340.3 1044.82   391.2 1069.45
   419.1  1080.3   441.4 1093.12   450.4 1097.31   462.6  1104.9     483 1114.53
#Mann= 6 ,-1,0
       0     .05       0  110.96      .1       0   206.1    .045       0
   240.1      .1       0  240.96     .06       0  379.85      .1       0
Bank Sta=206.1,240.1
XS Rating Curve= 0 ,0
Exp/Cntr(USF)=0,0
Exp/Cntr=0.3,0.1

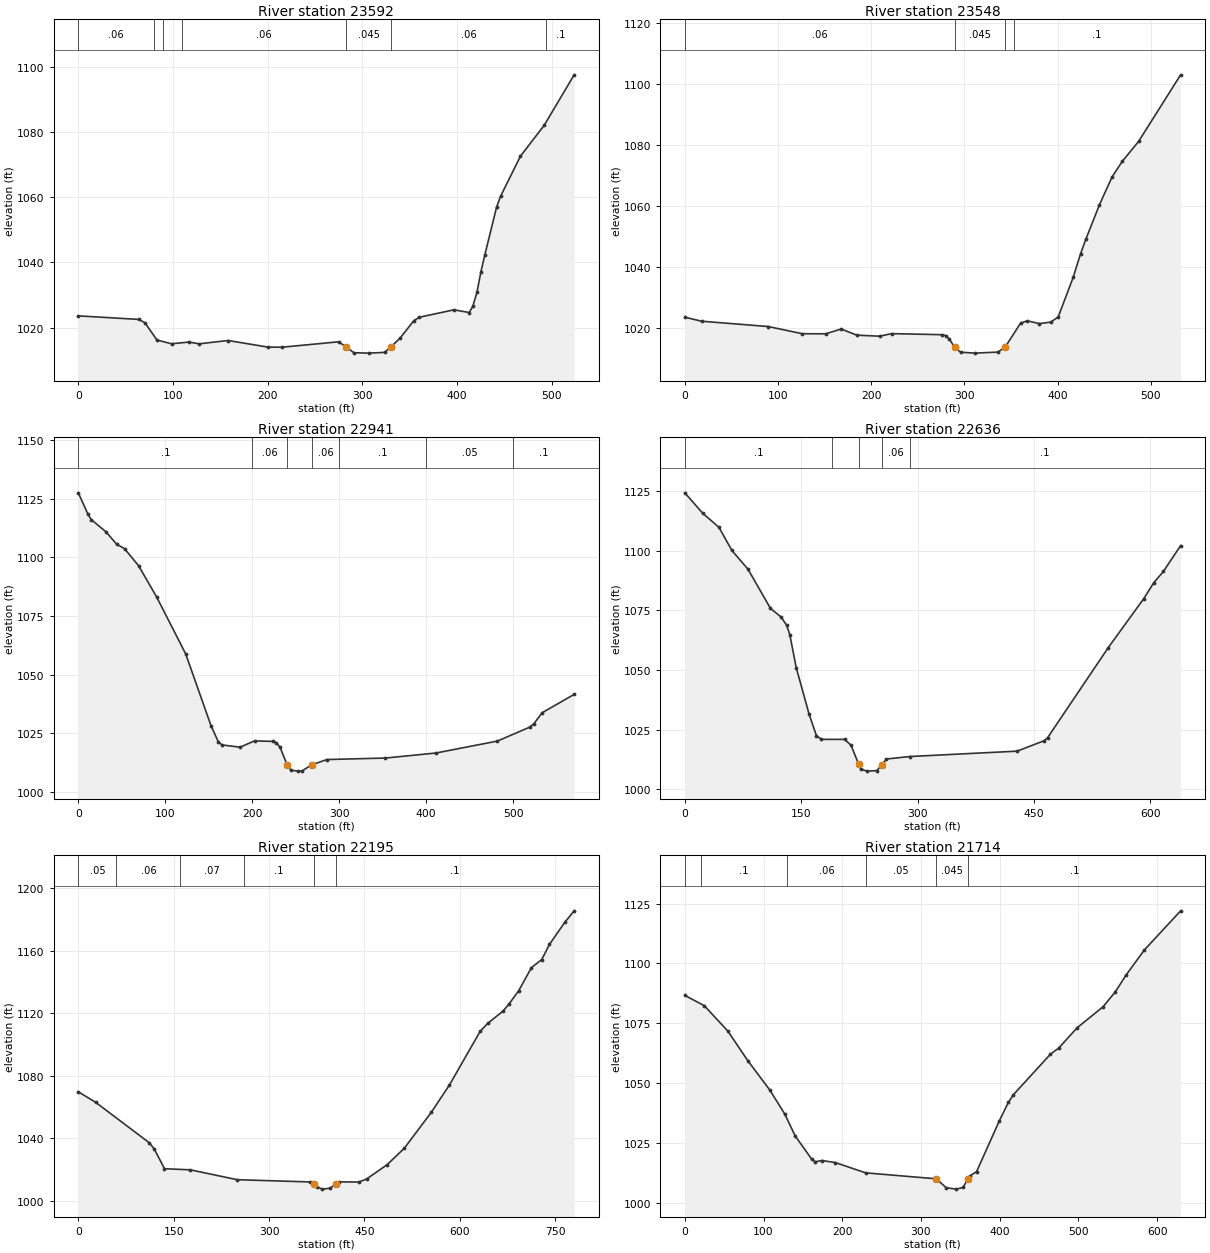
Type RM Length L Ch R = 1 ,23592   ,43.9,43.9,43.9
XS GIS Cut Line= 5
1690504.33977595421589.037784489 1690589.8394793421562.099521787
1690762.01011484421611.2911319391690915.44108936421638.229394641
1691010.31062322 421667.51011497
#Sta/Elev= 30
       0 1023.62      64 1022.53    70.4  1021.5    83.1  1016.2    98.5 1015.07
     117 1015.59   127.6 1015.05   158.2 1016.07   200.4 1014.04     215 1014.01
   274.9 1015.67     283 1014.12   291.1 1012.31   307.4  1012.2   323.6 1012.43
   330.31014.127   339.9  1016.8   354.5 1022.16   360.2 1023.19   396.7 1025.47
     413 1024.65   416.7 1026.52   421.1 1030.79   425.2 1036.99   429.4 1042.28
   441.9 1056.99   446.1  1060.3     467 1072.53   492.2 1082.04   523.8 1097.49
#Mann= 7 ,-1,0
       0     .06       0      80     .05       0   89.64     .08       0
  109.64     .06       0     283    .045       0   330.3     .06       0
  494.48      .1       0
Bank Sta=283,330.3
XS Rating Curve= 0 ,0
Exp/Cntr(USF)=0,0
Exp/Cntr=0.3,0.1

Type RM Length L Ch R = 1 ,23548   ,607.4,607.4,607.4
XS GIS Cut Line= 5
1690500.82608951421653.4553692121690576.95596236421606.606216686
1690743.27045383421655.7978268391690927.15337749421676.879945475
1691009.13939441421695.619606486
#Sta/Elev= 30
       0  1023.6      18 1022.28    89.4 1020.54   126.1 1018.18   151.1 1018.15
   167.8 1019.72   184.5 1017.71     209 1017.37     222 1018.21   275.8 1017.86
   279.8 1017.59   283.8 1016.44   289.5 1013.74   295.9 1012.12   311.2 1011.82
   336.1 1012.16   343.7 1013.79   360.3 1021.65   367.5 1022.41   380.4 1021.49
   392.5 1021.97   400.6 1023.65   416.7 1036.63   424.7 1044.44   430.4 1049.22
   444.9 1060.44   458.4 1069.53   469.4 1074.67   486.9  1081.2     532 1103.03
#Mann= 4 ,-1,0
       0     .06       0   289.5    .045       0   343.7     .06       0
  352.83      .1       0
Bank Sta=289.5,343.7
XS Rating Curve= 0 ,0
Exp/Cntr(USF)=0,0
Exp/Cntr=0.3,0.1

Type RM Length L Ch R = 1 ,22941   ,304.8,304.8,304.8
XS GIS Cut Line= 2
1690301.69846401422267.9444790771690848.79382283422107.768271364
#Sta/Elev= 30
       0 1127.44    11.1 1118.27      15 1115.98    31.7 1110.86    44.2 1105.51
    53.1 1103.65    69.2 1096.42      90 1083.09   123.4 1058.83   152.6 1028.19
   160.9 1021.38   165.1 1020.02   185.9 1019.05   202.6 1021.73   223.4 1021.53
   227.6 1020.97   231.8 1019.13   240.1  1011.5   244.3 1009.31     252 1008.85
   256.8 1008.85   268.4 1011.53   285.9 1013.79   352.9 1014.42     411 1016.56
   481.8 1021.65   519.3 1027.64   523.8 1029.06   533.4 1033.76   570.1 1041.55
#Mann= 7 ,-1,0
       0      .1       0     200     .06       0   240.1    .045       0
   268.4     .06       0     300      .1       0     400     .05       0
     500      .1       0
Bank Sta=240.1,268.4
XS Rating Curve= 0 ,0
Exp/Cntr(USF)=0,0
Exp/Cntr=0.3,0.1

Type RM Length L Ch R = 1 ,22636   ,441,441,441
XS GIS Cut Line= 2
 1690405.7089885422550.8531056881691021.45129348422380.275845526
#Sta/Elev= 30
       0 1124.19    23.2  1115.6      44 1109.75    60.6 1100.07    81.4  1092.2
   110.4 1075.76   124.1 1072.14   131.2 1068.74   135.3 1064.76   143.6  1050.9
   160.2  1031.4   169.6 1022.42   176.1 1020.87   205.9 1020.86   214.2 1018.42
     224 1010.49   226.6 1008.43   234.9 1007.56   247.4 1007.77   254.1 1010.31
   259.8 1012.63   289.9 1013.68   428.2 1015.93   463.2 1020.33   467.4 1021.53
   545.5 1059.25   591.5  1079.9   604.3  1086.5   616.8 1091.29   638.9 1102.07
#Mann= 5 ,-1,0
       0      .1       0     190     .06       0     224    .045       0
   254.1     .06       0     290      .1       0
Bank Sta=224,254.1
XS Rating Curve= 0 ,0
Exp/Cntr(USF)=0,0
Exp/Cntr=0.3,0.1

Type RM Length L Ch R = 1 ,22195   ,480.9,480.9,480.9
XS GIS Cut Line= 4
1690428.92766606422940.9374713071690549.11760547422940.937471307
1691002.14122325422853.1063617381691198.60554728422878.531156613
#Sta/Elev= 30
       0 1069.63    27.2 1062.95   111.2 1037.16   119.2 1033.22   135.5 1020.43
   176.2 1019.71   249.8  1013.4   363.6 1011.97   371.1 1010.82   375.9 1008.61
     384 1007.36   396.2 1007.97   405.31010.779   409.8 1012.02   441.1 1011.88
   453.3 1013.81   485.9 1023.08   512.7 1033.55   555.1 1056.52   583.6 1073.98
     632 1108.41   644.1 1113.55     668 1121.35   677.3 1125.84   692.5 1134.33
   712.7 1149.19   728.8  1154.3   740.9    1164   765.1 1178.15   779.8 1185.51
#Mann= 6 ,-1,0
       0     .05       0      60     .06       0  160.19     .07       0
  260.19      .1       0   371.1    .045       0   405.3      .1       0
Bank Sta=371.1,405.3
XS Rating Curve= 0 ,0
Exp/Cntr(USF)=0,0
Exp/Cntr=0.3,0.1

Type RM Length L Ch R = 1 ,21714   ,468,468,468
XS GIS Cut Line= 3
1690368.83269636 423209.053489991690821.85631413423377.781674162
1690965.15970343423347.734189309
#Sta/Elev= 30
       0 1086.62    24.8 1082.32    54.7 1071.69    80.3 1059.22   107.9 1047.12
   127.3 1036.87   140.1 1027.96   161.4 1018.07   165.7 1017.08   174.2 1017.62
   191.3 1016.75   229.7 1012.46   319.4 1009.97   332.2 1006.22     345 1005.66
   353.5 1006.37   359.8 1010.03     362 1011.15   370.6 1012.96   399.6 1034.26
   411.1 1041.96   417.5 1045.16   464.5 1062.07   474.9 1064.58     498 1072.99
   531.3 1081.87   546.8 1088.08   560.7  1095.2   583.8 1105.63   629.8 1121.96
#Mann= 6 ,-1,0
       0     .05       0      20      .1       0     130     .06       0
     230     .05       0   319.4    .045       0   359.8      .1       0
Bank Sta=319.4,359.8
XS Rating Curve= 0 ,0
Exp/Cntr(USF)=0,0
Exp/Cntr=0.3,0.1

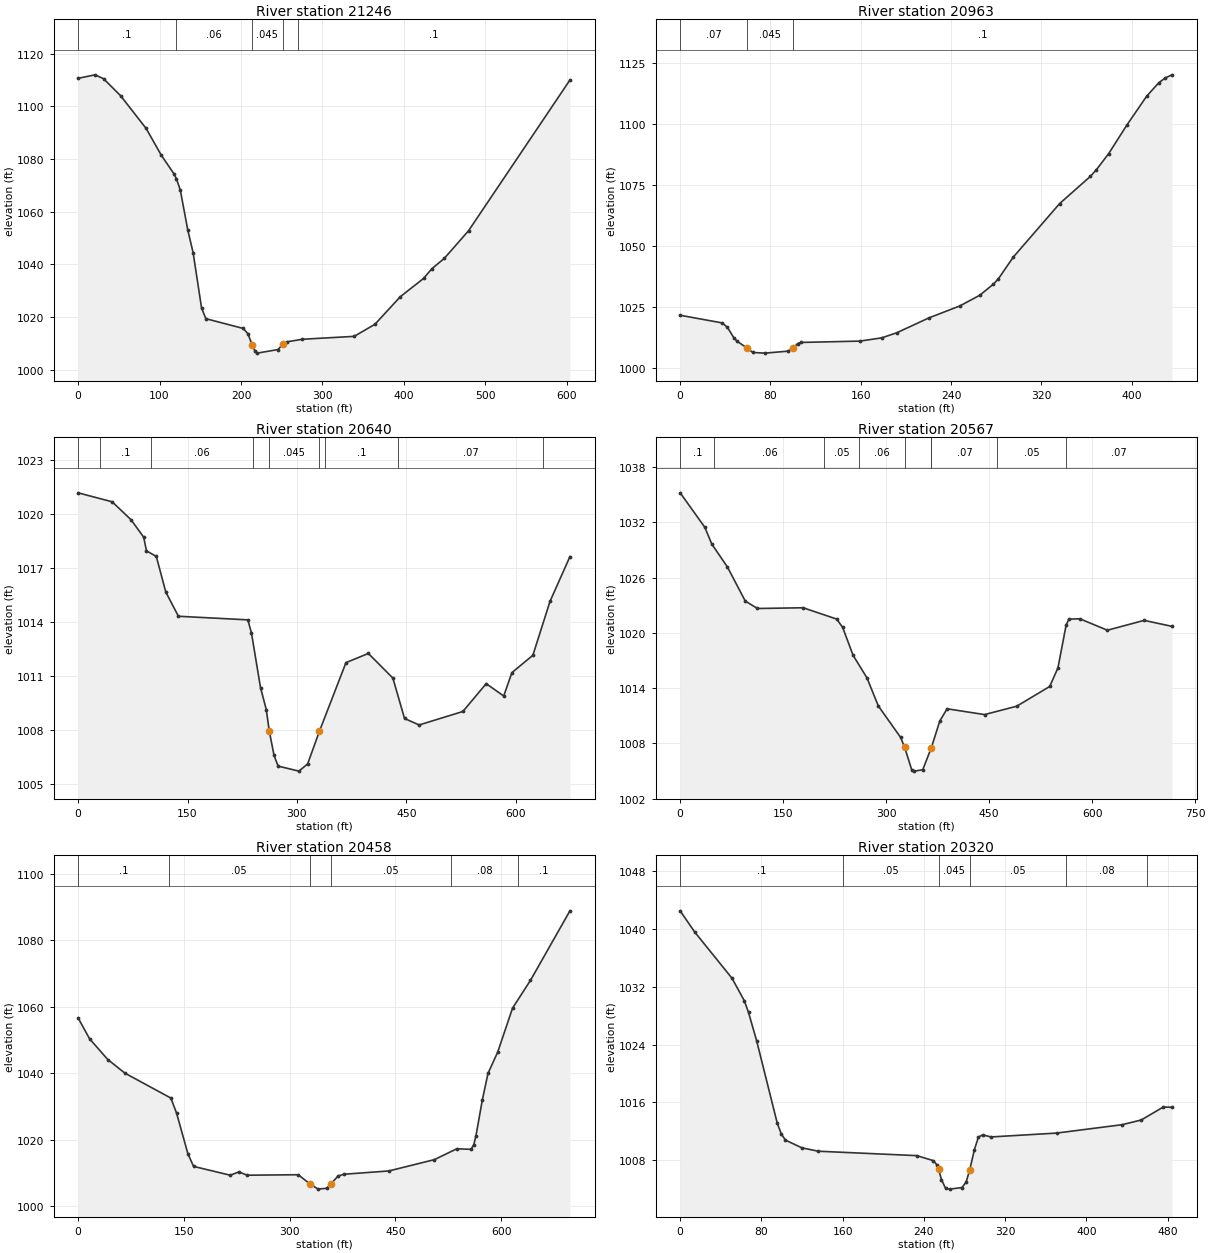
Type RM Length L Ch R = 1 ,21246   ,282.6,282.6,282.6
XS GIS Cut Line= 3
1690606.18546286423920.328147792 1690892.6304473 423581.64907795
1691015.63329356423478.865877649
#Sta/Elev= 30
       0 1110.67    20.7    1112    31.2 1110.53    52.1 1104.08    83.5 1091.63
   102.1 1081.47   117.6 1074.43   120.7 1072.53   125.5 1068.16   134.6 1053.11
   141.2 1044.45   151.6 1023.38   156.9 1019.36   202.7 1015.66   208.4 1013.69
   213.6 1009.51   216.9 1007.24   219.8 1006.28   245.3 1007.63   251.2 1009.57
   256.4 1010.58   275.5 1011.55     339 1012.65   364.5 1017.25   395.7 1027.74
   424.1 1034.63   434.5 1038.38   449.7 1042.29   479.4 1052.77   603.9 1110.03
#Mann= 5 ,-1,0
       0      .1       0     120     .06       0   213.6    .045       0
   251.2     .06       0     270      .1       0
Bank Sta=213.6,251.2
XS Rating Curve= 0 ,0
Exp/Cntr(USF)=0,0
Exp/Cntr=0.3,0.1

Type RM Length L Ch R = 1 ,20963   ,323.8,323.8,323.8
XS GIS Cut Line= 2
1690920.40615368423979.9817230831691215.20859179423659.247589031
#Sta/Elev= 30
       0 1021.51    37.3 1018.36    41.9 1016.52    47.5 1012.29    50.4 1010.86
    59.1 1008.09    64.5 1006.22    75.3 1005.96    95.7 1006.78   100.1 1008.05
   104.1  1009.9     107 1010.35   159.2  1010.9   178.5 1012.23   191.9 1014.33
   220.2 1020.41   247.8 1025.36   265.5 1029.77   277.4 1034.29   281.8 1036.45
   295.1 1045.43   336.1 1067.38   363.3 1078.54   368.7  1081.3   379.6 1087.94
   395.7 1099.66   413.3 1111.55     424 1117.04   429.7 1118.98   435.6 1120.26
#Mann= 3 ,-1,0
       0     .07       0    59.1    .045       0   100.1      .1       0
Bank Sta=59.1,100.1
XS Rating Curve= 0 ,0
Exp/Cntr(USF)=0,0
Exp/Cntr=0.3,0.1

Type RM Length L Ch R = 1 ,20640   ,73.1,73.1,73.1
XS GIS Cut Line= 4
1690952.98546037423993.3080214821691182.73267612424088.098830776
1691330.54207366424110.5915651851691606.88138211424112.198189071
#Sta/Elev= 30
       0 1021.18    46.7 1020.68    72.6 1019.68    89.9 1018.71    93.7 1017.95
   107.2 1017.64   120.2 1015.66   137.5 1014.31   232.7 1014.11   237.7 1013.38
   250.1 1010.34     258 1009.12   262.1 1007.92   268.7 1006.56   274.2 1005.97
   302.8 1005.69   314.7 1006.09   330.9 1007.91   367.3 1011.73     398 1012.24
   431.6 1010.87   447.6 1008.62   467.6 1008.26   527.6 1009.01   559.6 1010.56
   583.6 1009.87   594.8 1011.17   623.6 1012.14   647.1 1015.14   674.4 1017.63
#Mann= 9 ,-1,0
       0     .07       0      30      .1       0     100     .06       0
     240     .07       0   262.1    .045       0   330.9     .07       0
  338.53      .1       0  438.04     .07       0  638.04      .1       0
Bank Sta=262.1,330.9
XS Rating Curve= 0 ,0
Exp/Cntr(USF)=0,0
Exp/Cntr=0.3,0.1

Type RM Length L Ch R = 1 ,20567   ,108.2,108.2,108.2
XS GIS Cut Line= 4
1690938.52584539424038.2934902991691187.55254777424157.183657889
1691341.78844086424179.6763922981691626.16086875424173.249896753
#Sta/Elev= 30
       0  1035.2    35.9 1031.46    46.1 1029.63    68.9 1027.14    94.8 1023.45
   112.6 1022.64   179.1 1022.72     228 1021.49   236.7 1020.58   251.9 1017.55
   272.1  1015.1   288.6 1012.06     321 1008.65   326.9 1007.58   337.2 1005.13
   341.2 1004.98   353.3 1005.13   365.91007.538   378.2 1010.43   388.8 1011.75
   443.3 1011.12   490.2 1012.03   538.2 1014.17   550.2 1016.18   562.2 1020.85
   566.2 1021.49   582.2 1021.52   622.2 1020.28   675.8 1021.35   716.3  1020.7
#Mann= 9 ,-1,0
       0      .1       0      50     .06       0     210     .05       0
     260     .06       0   326.9    .045       0   365.9     .06       0
  365.95     .07       0  461.82     .05       0  561.82     .07       0
Bank Sta=326.9,365.9
XS Rating Curve= 0 ,0
Exp/Cntr(USF)=0,0
Exp/Cntr=0.3,0.1

Type RM Length L Ch R = 1 ,20458   ,138.3,138.3,138.3
XS GIS Cut Line= 4
1690952.63235855424273.5331226021691037.25157689424247.601426657
1691531.31862594424291.2758619321691633.68058362424339.044775515
#Sta/Elev= 30
       0 1056.59    16.2 1050.34      42 1044.09    66.4 1039.98   131.5 1032.49
   139.6 1027.97   155.6 1015.78   163.7 1011.93   215.9 1009.27   227.9 1010.29
   239.6 1009.28   312.2 1009.42   328.3 1006.74   340.3 1005.09   352.4 1005.35
     3591006.734   368.5 1009.01   376.5 1009.56   440.7 1010.56   505.2 1013.96
   537.1 1017.23   557.2 1017.06   561.2 1018.48   564.3 1021.19   573.2 1031.85
   581.3 1039.91   595.1 1046.33   616.1 1059.54   641.5 1067.89   697.5 1088.82
#Mann= 6 ,-1,0
       0      .1       0   128.5     .05       0   328.3    .045       0
     359     .05       0   528.5     .08       0   624.5      .1       0
Bank Sta=328.3,359
XS Rating Curve= 0 ,0
Exp/Cntr(USF)=0,0
Exp/Cntr=0.3,0.1

Type RM Length L Ch R = 1 ,20320   ,52.9,52.9,52.9
XS GIS Cut Line= 2
1691017.58818132424366.9161378631691496.62076589424438.361095465
#Sta/Elev= 30
       0 1042.44    14.2 1039.54    51.1 1033.13    63.2 1030.03    67.3 1028.43
    75.4 1024.47    95.6 1013.15    99.6 1011.65   103.7 1010.81   119.8 1009.75
     136 1009.28   233.1 1008.67   249.3 1007.98   253.3 1007.32   254.41006.796
   257.3 1005.37   261.4 1004.14   265.4 1004.05   277.6 1004.27   281.6 1005.03
   285.2 1006.72   289.7 1009.48   293.7 1011.23   297.8 1011.53   306.3 1011.25
   370.6 1011.78   435.3 1012.94   454.1 1013.59   475.7 1015.37   484.3 1015.34
#Mann= 6 ,-1,0
       0      .1       0     160     .05       0   254.4    .045       0
   285.2     .05       0     380     .08       0     460     .07       0
Bank Sta=254.4,285.2
XS Rating Curve= 0 ,0
Exp/Cntr(USF)=0,0
Exp/Cntr=0.3,0.1

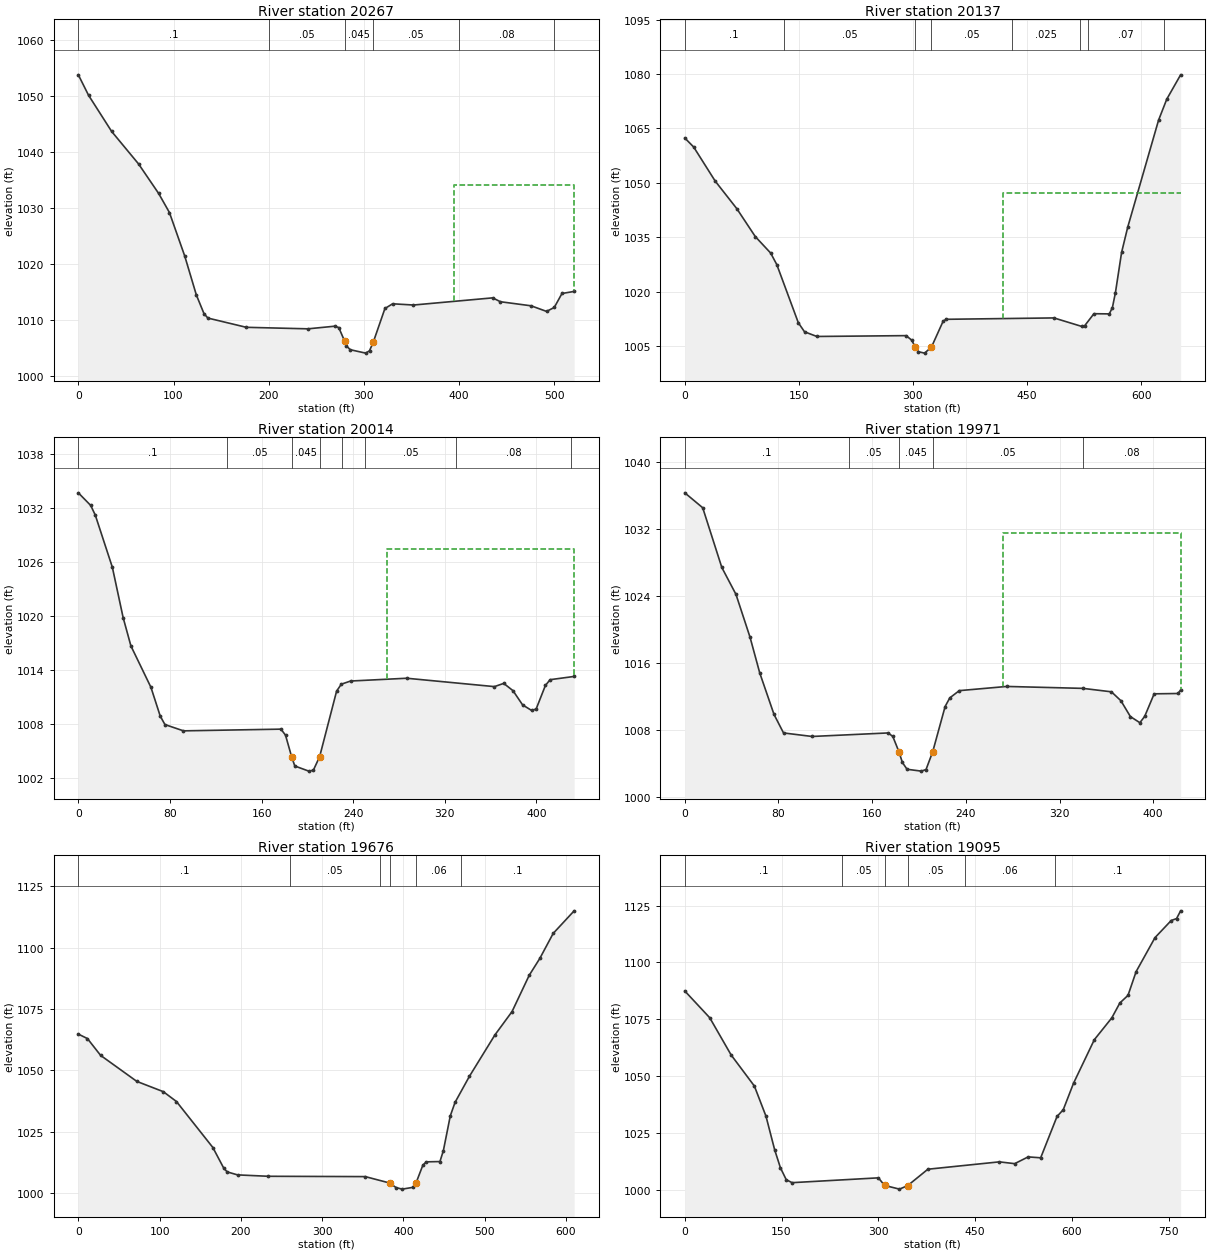
Type RM Length L Ch R = 1 ,20267   ,129.9,129.9,129.9
XS GIS Cut Line= 2
1690981.48344248424415.3930959341691496.82412026424491.522968788
#Sta/Elev= 30
       0  1053.7    10.7 1050.06      35 1043.59    63.3 1037.78    84.4 1032.51
    95.7 1029.11   111.8 1021.33     124 1014.38     132 1011.06   136.1 1010.26
   176.5 1008.61   241.2 1008.34   269.5 1008.81   273.6 1008.57   279.91006.087
   281.6 1005.29   285.7 1004.61   301.9    1004   305.9 1004.42     310 1006.03
   322.1 1011.97   330.2 1012.81   352.1 1012.59   435.3 1013.87   443.4 1013.18
   475.7 1012.45   491.9 1011.45     500 1012.16   508.1 1014.65   520.9 1015.02
#Mann= 6 ,-1,0
       0      .1       0     200     .05       0   279.9    .045       0
     310     .05       0     400     .08       0     500     .07       0
#XS Ineff= 2 , 0
                          394.25         1033.99
Permanent Ineff=
       F       F
Bank Sta=279.9,310
XS Rating Curve= 0 ,0
Exp/Cntr(USF)=0,0
Exp/Cntr=0.3,0.1

Type RM Length L Ch R = 1 ,20137   ,123.7,123.7,123.7
XS GIS Cut Line= 2
1690948.53788024 424539.674212561691592.73580055424639.306518031
#Sta/Elev= 30
       0 1062.37    11.7 1059.87      40 1050.48    68.4 1042.89    92.7  1035.2
   112.9 1030.66     121 1027.46   149.3 1011.44   157.4 1008.97   173.6 1007.68
     291 1007.91   298.3 1006.67   303.1 1004.73   307.2 1003.47   315.3 1003.09
   324.31004.753   339.6 1011.86   343.6 1012.41   485.3 1012.79   521.7 1010.46
   525.8 1010.65   537.9 1013.95   558.1  1013.9   562.2 1015.63   566.2 1019.77
   574.3 1030.85   582.4 1037.84   622.9 1067.28   633.7 1073.07   651.9 1079.77
#Mann= 8 ,-1,0
       0      .1       0     130     .05       0   303.1    .045       0
   324.3     .05       0     430    .025       0     520      .1       0
     530     .07       0     630      .1       0
#XS Ineff= 2 , 0
                          418.69          1047.1
Permanent Ineff=
       F       F
Bank Sta=303.1,324.3
XS Rating Curve= 0 ,0
Exp/Cntr(USF)=0,0
Exp/Cntr=0.3,0.1

Type RM Length L Ch R = 1 ,20014   ,43,43,43
XS GIS Cut Line= 2
1691045.48267129424678.4963700011691472.91154062424747.400368594
#Sta/Elev= 30
       0 1033.67    10.8 1032.27    14.8  1031.2    29.7 1025.41    39.1 1019.83
    45.9 1016.68    63.4 1012.08    71.5 1008.89    75.6 1007.95    91.8 1007.25
   176.9 1007.44   180.9 1006.77   186.21004.384     189 1003.35   201.2 1002.78
   205.2 1002.88   210.71004.395   225.5 1011.66   229.6 1012.43   237.7 1012.78
   286.7 1013.09   363.3 1012.16   371.4 1012.52   379.5 1011.71   387.9 1010.13
   395.7 1009.52   399.7 1009.67   407.8 1012.29   411.9 1012.93   432.9 1013.29
#Mann= 8 ,-1,0
       0      .1       0     130     .05       0   186.2    .045       0
   210.7     .05       0     230      .1       0     250     .05       0
     330     .08       0     430     .06       0
#XS Ineff= 2 , 0
                          269.23         1027.39
Permanent Ineff=
       F       F
Bank Sta=186.2,210.7
XS Rating Curve= 0 ,0
Exp/Cntr(USF)=0,0
Exp/Cntr=0.3,0.1

Type RM Length L Ch R = 1 ,19971   ,295.1,295.1,295.1
XS GIS Cut Line= 2
1691041.00111041424719.3906130681691458.34646775424790.535392104
#Sta/Elev= 30
       0 1036.27    15.3 1034.49    31.6 1027.38    43.7 1024.17    55.7 1019.07
      64 1014.81    76.2 1009.86    84.3 1007.66   108.7 1007.24   173.6 1007.66
   177.6 1007.25   182.91005.401   185.8 1004.14   189.8 1003.33     202 1003.11
     206  1003.3   211.7 1005.42   222.3 1010.81   226.3 1011.84   234.4  1012.7
     275  1013.2     340 1012.97   364.3 1012.56   372.4  1011.5   380.5 1009.61
   388.6 1008.88   392.7 1009.63   400.8 1012.32   421.1 1012.36   423.4 1012.77
#Mann= 5 ,-1,0
       0      .1       0     140     .05       0   182.9    .045       0
   211.7     .05       0     340     .08       0
#XS Ineff= 2 , 0
                          272.11         1031.48
Permanent Ineff=
       F       F
Bank Sta=182.9,211.7
XS Rating Curve= 0 ,0
Exp/Cntr(USF)=0,0
Exp/Cntr=0.3,0.1

Type RM Length L Ch R = 1 ,19676   ,580.3,580.3,580.3
XS GIS Cut Line= 3
1690921.06700625424924.4772284491691059.86982086424947.815754799
  1691504.530165425097.673660837
#Sta/Elev= 30
       0 1064.73    11.2 1062.91    27.4 1056.07      72 1045.46   104.5 1041.29
   120.7 1037.28   165.5 1018.54     179 1010.07   183.2  1008.6   195.9 1007.39
   233.9 1006.82     353 1006.69   383.21004.063   390.9 1002.21   398.5 1001.59
   411.2 1002.29   415.4 1004.05   423.8 1011.29     428  1012.7   444.9 1012.82
   449.1 1017.27   457.6 1031.42   463.5 1036.95   481.2 1047.57   512.5 1064.39
   533.6 1073.91   554.7 1088.68   567.7 1095.53   584.2 1105.74     610 1114.94
#Mann= 6 ,-1,0
       0      .1       0  260.75     .05       0  370.75     .06       0
   383.2    .045       0   415.4     .06       0  470.75      .1       0
Bank Sta=383.2,415.4
XS Rating Curve= 0 ,0
Exp/Cntr(USF)=0,0
Exp/Cntr=0.3,0.1

Type RM Length L Ch R = 1 ,19095   ,373.1,373.1,373.1
XS GIS Cut Line= 4
1690668.75103681425307.6072782221690751.66422253425351.827643938
1691179.49626083425568.5074359471691366.12385516 425510.97286397
#Sta/Elev= 30
       0 1087.46    38.7 1075.68    71.8 1059.35   107.9 1045.66   125.9 1032.39
   139.3 1017.68   148.3 1009.71   157.3  1004.5   166.3 1003.19   300.2 1005.31
   309.7 1001.98   332.9 1000.35   345.6  1001.9   376.9  1009.1   487.7 1012.34
   511.5 1011.55   532.4 1014.52   551.8 1014.12   577.2 1032.32   586.8 1035.25
   602.8 1046.94     635 1066.05   662.1 1075.64   674.6  1082.2   687.2 1085.53
   699.8 1095.98   729.1 1110.93   754.2 1118.44   762.5 1119.29   768.8  1122.7
#Mann= 6 ,-1,0
       0      .1       0  243.97     .05       0   309.7    .045       0
   345.6     .05       0  433.97     .06       0  573.54      .1       0
Bank Sta=309.7,345.6
XS Rating Curve= 0 ,0
Exp/Cntr(USF)=0,0
Exp/Cntr=0.3,0.1