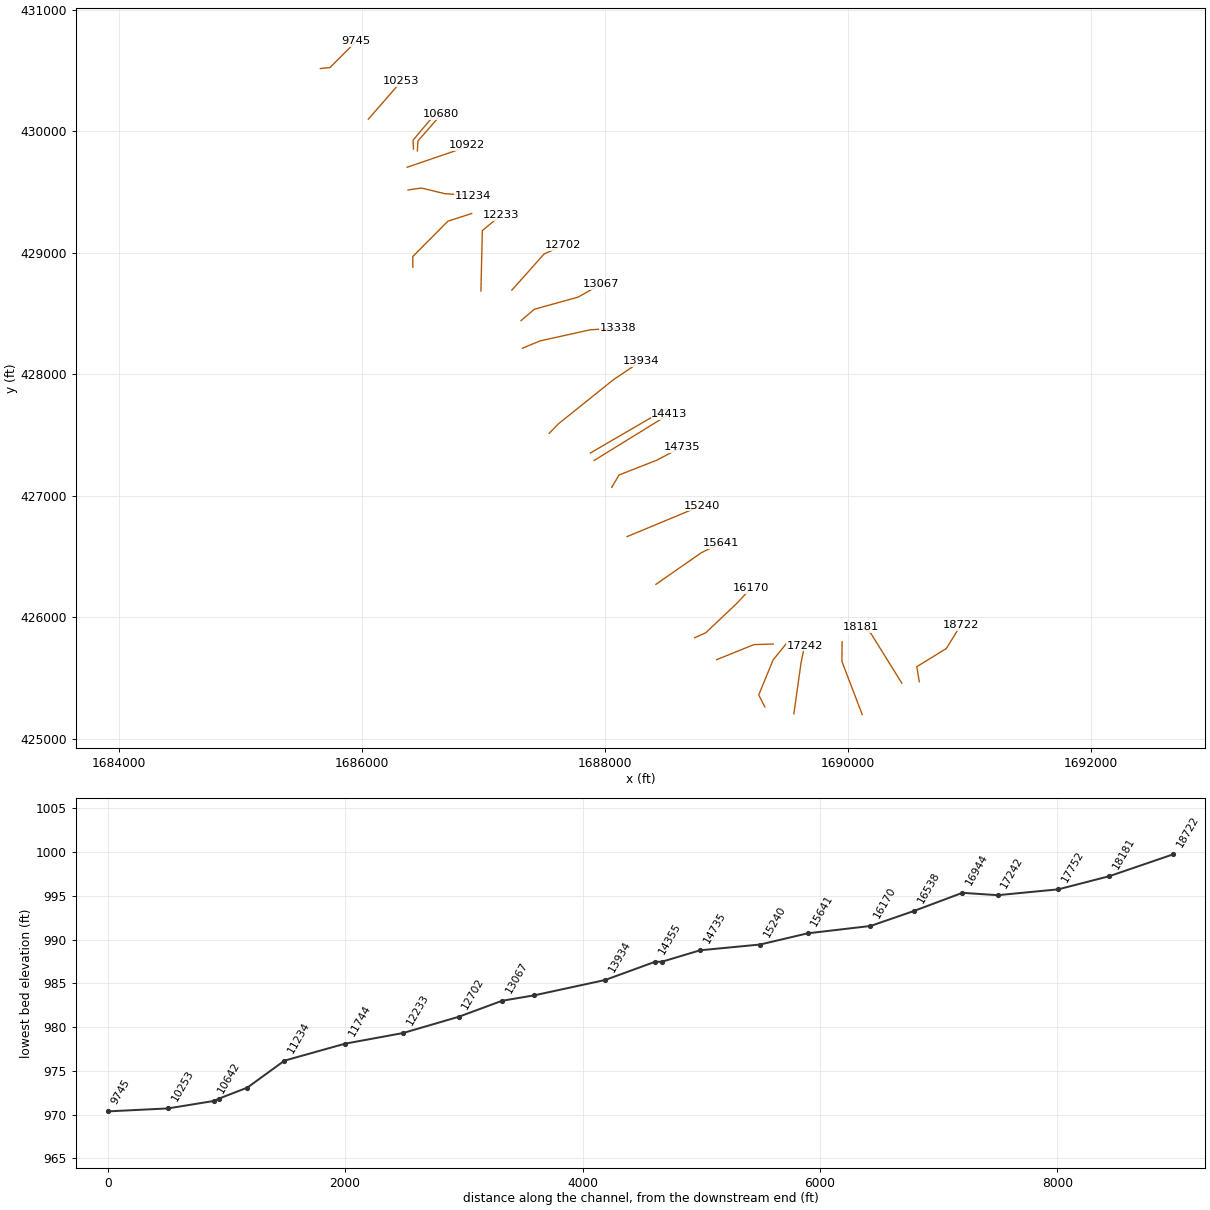
HEC-RAS study LNGDRN.prj: LNGDRN

--- LNGDRN.g01 (geometry) --- (continued)

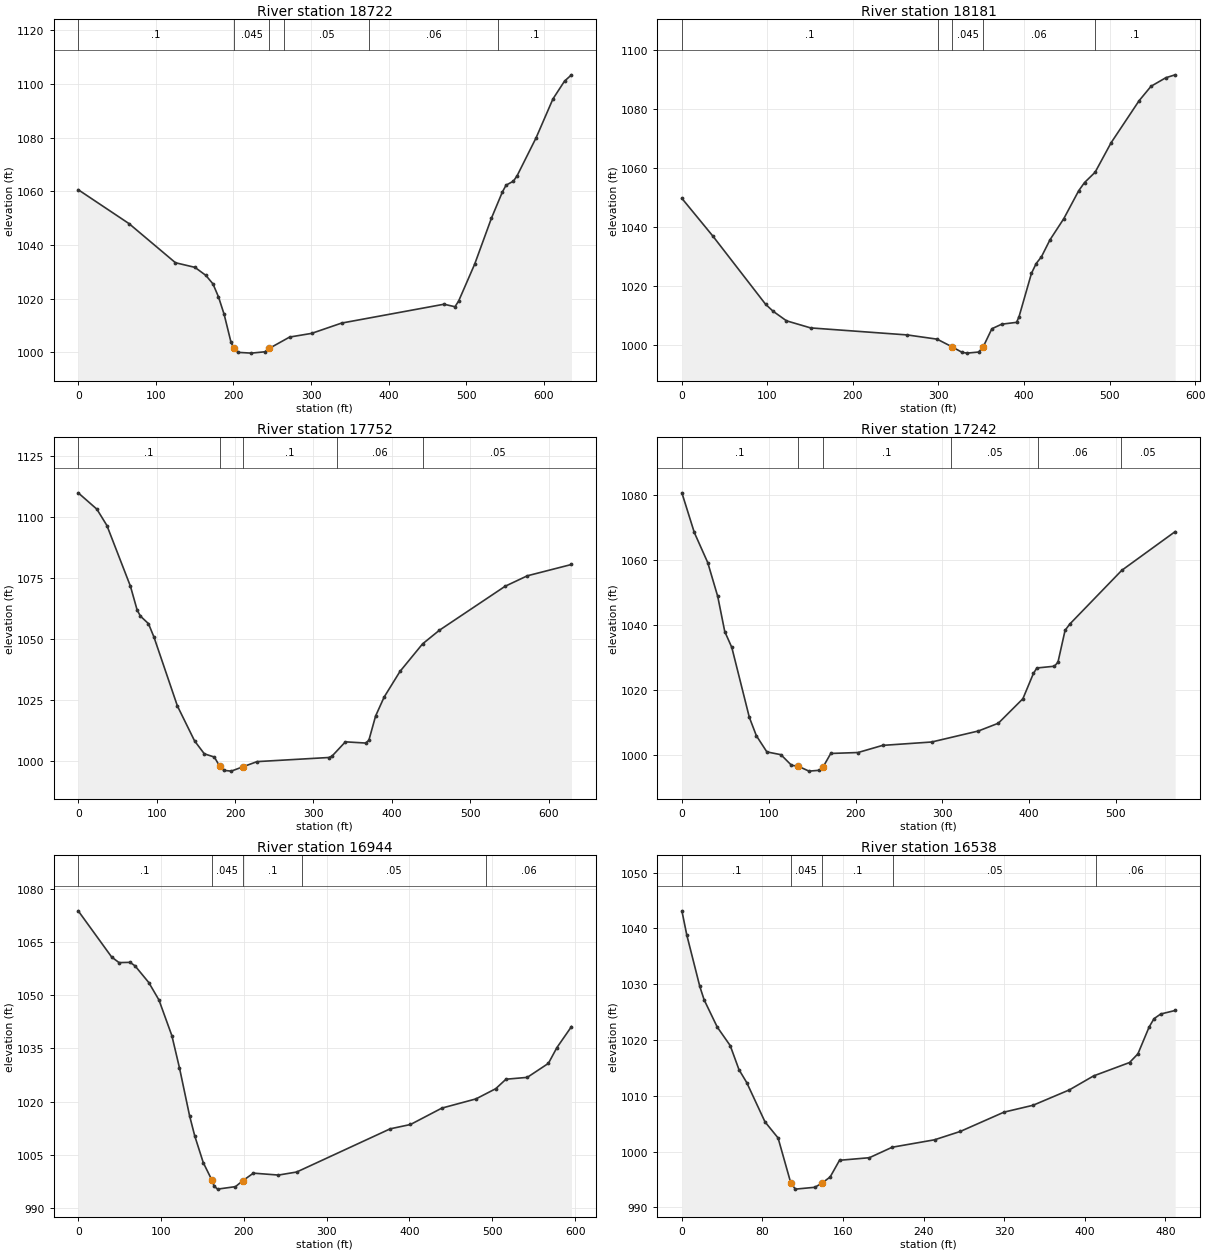
Type RM Length L Ch R = 1 ,18722   ,540.9,540.9,540.9
XS GIS Cut Line= 4
1690587.29304778425467.9125068311690566.69896393425591.477009924
1690810.08359124425741.2521651891690928.03152601425932.215488152
#Sta/Elev= 30
       0 1060.58    65.5 1047.95   125.3  1033.4   150.4 1031.68   164.5 1028.68
   173.6 1025.53   180.7 1020.71     188  1014.2   196.8 1003.87   200.31001.673
   205.6 1000.05     223  999.76   240.5 1000.26   246.3 1001.55   272.4 1005.74
   300.7 1007.11   339.3 1010.94   471.3 1017.96   485.4 1017.02   490.1 1019.14
   510.8  1032.9   532.4 1050.01   546.5 1059.76   551.2 1062.26   560.7 1063.77
   565.4 1065.75     590 1079.96   611.6 1094.36   626.5 1100.98   635.5 1103.33
#Mann= 6 ,-1,0
       0      .1       0   200.3    .045       0   246.3      .1       0
  265.27     .05       0  375.27     .06       0  541.05      .1       0
Bank Sta=200.3,246.3
XS Rating Curve= 0 ,0
Exp/Cntr(USF)=0,0
Exp/Cntr=0.3,0.1

Type RM Length L Ch R = 1 ,18181   ,429.2,429.2,429.2
XS GIS Cut Line= 3
1690443.13446084425456.6793701861690188.51669689425866.688857723
1690108.01255093425915.365783184
#Sta/Elev= 30
       0 1049.65    36.1 1036.92    97.9 1013.78   106.7 1011.42   122.3 1008.19
   150.5 1005.79   263.5 1003.41   298.4 1001.98   315.8  999.39   327.4  997.54
   333.2  997.25   346.9  997.62   352.3999.3972   362.4  1005.5   373.9 1007.05
   391.3 1007.67   394.2 1009.62   408.7 1024.27   414.2 1027.58   420.4 1029.89
   430.3 1035.59   446.5 1042.78   463.9 1052.22   470.7 1054.99   483.1 1058.49
   501.8 1068.48   534.5  1082.7   548.5  1087.6   565.8 1090.49   576.7 1091.47
#Mann= 5 ,-1,0
       0      .1       0     300     .06       0   315.8    .045       0
   352.3     .06       0  482.64      .1       0
Bank Sta=315.8,352.3
XS Rating Curve= 0 ,0
Exp/Cntr(USF)=0,0
Exp/Cntr=0.3,0.1

Type RM Length L Ch R = 1 ,17752   ,509.7,509.7,509.7
XS GIS Cut Line= 3
1690117.55763529 425198.333406771689950.74555611425634.740765422
1689952.43052661425796.497933108
#Sta/Elev= 30
       0 1109.87    23.8 1103.17    36.6 1096.47    66.6 1071.57    75.2 1061.75
    79.4  1059.3    89.6 1056.22    96.6 1050.72   126.5 1022.46   148.4 1008.14
   160.8 1002.85   173.6 1001.52   180.6997.6557   185.6  996.07   195.1  995.75
   210.4  997.57   228.1  999.65   319.2 1001.33   323.5 1001.86   340.7 1007.76
   366.4 1007.27   370.6 1008.37   379.2 1018.34   390.1 1026.12   410.3 1036.63
   439.1 1047.93   460.6 1053.53   544.4 1071.56   572.7 1075.85     629 1080.49
#Mann= 5 ,-1,0
       0      .1       0   180.6    .045       0   210.4      .1       0
     330     .06       0     440     .05       0
Bank Sta=180.6,210.4
XS Rating Curve= 0 ,0
Exp/Cntr(USF)=0,0
Exp/Cntr=0.3,0.1

Type RM Length L Ch R = 1 ,17242   ,298.3,298.3,298.3
XS GIS Cut Line= 3
1689555.36503328425203.5926411571689614.50749771425625.172259438
1689643.32049321425764.687816567
#Sta/Elev= 30
       0 1080.61    14.3 1068.43    29.8 1059.16    41.3 1048.77    49.4 1037.96
    57.5  1033.1    77.7 1011.61    85.8 1005.96    97.9 1000.99   114.1 1000.13
   126.2  996.89   134.2  996.56   146.4  995.08   158.5  995.34   162.9996.4807
   171.5 1000.51   202.9  1000.8   231.2 1002.99   287.7 1004.03   341.6 1007.42
   364.5  1009.8   392.8 1017.33   404.9 1025.09   408.9 1026.78   429.1 1027.32
   433.2 1028.57   441.4 1038.36   446.8 1040.27   506.7 1056.79   568.2 1068.69
#Mann= 6 ,-1,0
       0      .1       0   134.2    .045       0   162.9      .1       0
     310     .05       0     410     .06       0  505.71     .05       0
Bank Sta=134.2,162.9
XS Rating Curve= 0 ,0
Exp/Cntr(USF)=0,0
Exp/Cntr=0.3,0.1

Type RM Length L Ch R = 1 ,16944   ,406.4,406.4,406.4
XS GIS Cut Line= 4
 1689316.2707985 425260.533852791689266.22717475425359.104626849
1689384.51210362425647.2345817891689493.69819181425782.200718577
#Sta/Elev= 30
       0 1073.72    40.4 1060.71    49.3 1059.14    62.6 1059.21    68.6 1058.23
    85.2 1053.53    97.5 1048.61   113.1 1038.56   122.3 1029.47   134.5 1015.98
   140.7 1010.34     151 1002.81   161.6997.7995     164  996.22   168.3  995.35
   189.9  996.05   198.6   997.7   211.5  999.85   241.8  999.31   263.8 1000.17
   376.7 1012.33   401.2 1013.55   439.1 1018.17   480.3 1020.76   504.1 1023.63
   516.5  1026.3   542.2 1026.82   567.7 1030.76     578 1035.21   595.6 1041.13
#Mann= 5 ,-1,0
       0      .1       0   161.6    .045       0   198.6      .1       0
  270.55     .05       0  492.01     .06       0
Bank Sta=161.6,198.6
XS Rating Curve= 0 ,0
Exp/Cntr(USF)=0,0
Exp/Cntr=0.3,0.1

Type RM Length L Ch R = 1 ,16538   ,367.3,367.3,367.3
XS GIS Cut Line= 3
1688919.58672563425649.2940317781689226.67259866425773.356724482
1689385.12890914 425778.27009845
#Sta/Elev= 30
       0 1043.16     4.9 1038.81    17.8  1029.6    22.1  1027.2    35.1 1022.33
      48    1019    56.7 1014.69    64.4 1012.37    82.5 1005.34    95.5 1002.45
   108.2 994.332   112.7  993.28     132  993.61     139 994.345   147.2  995.46
   156.5  998.45   186.1  998.91   208.8 1000.79   250.8 1002.12   276.4 1003.62
   319.8 1007.08   348.6 1008.31   384.7 1011.07   408.7 1013.57   444.4 1015.97
   452.7 1017.52   463.8 1022.32   468.7 1023.83   475.4 1024.67   489.7  1025.3
#Mann= 5 ,-1,0
       0      .1       0   108.2    .045       0     139      .1       0
     210     .05       0   411.2     .06       0
Bank Sta=108.2,139
XS Rating Curve= 0 ,0
Exp/Cntr(USF)=0,0
Exp/Cntr=0.3,0.1

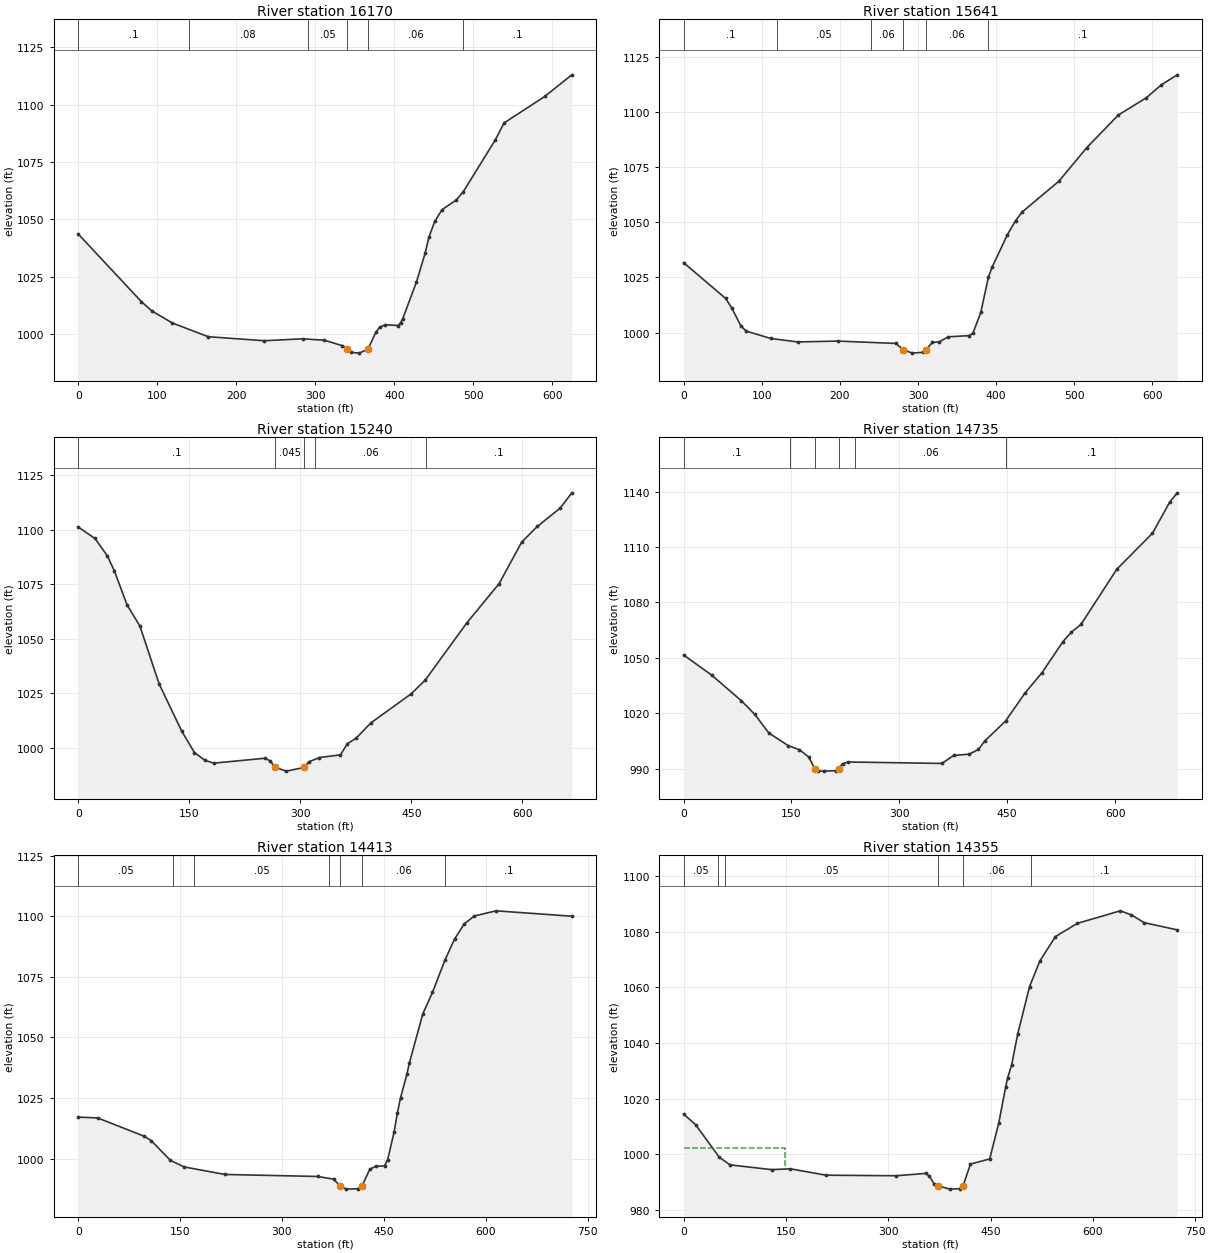
Type RM Length L Ch R = 1 ,16170   ,529.5,529.5,529.5
XS GIS Cut Line= 4
1688739.28808482425830.1770753721688830.73143367425871.121858442
1689090.04839312426116.7905568651689203.32895962426239.624906077
#Sta/Elev= 30
       0 1043.54    79.8 1014.08    92.9 1010.01   119.1 1004.72   164.4  998.73
   235.2  996.97   283.9  997.81   311.5  997.19   334.2   994.8   340.7  993.32
   345.5  991.91   355.6  991.56   366.6   993.3   376.6 1000.65   381.4 1002.85
   388.6 1003.96   404.9  1003.6   407.8 1004.79   410.7 1006.65     428 1022.66
   438.9 1035.12   443.7 1042.16   451.2 1049.11   460.4 1054.19   478.5 1058.43
     487 1061.91   527.8 1084.65   538.7 1091.98   590.3 1103.58   624.5 1113.01
#Mann= 6 ,-1,0
       0      .1       0  140.19     .08       0  290.19     .05       0
   340.7    .045       0   366.6     .06       0   487.4      .1       0
Bank Sta=340.7,366.6
XS Rating Curve= 0 ,0
Exp/Cntr(USF)=0,0
Exp/Cntr=0.3,0.1

Type RM Length L Ch R = 1 ,15641   ,400.3,400.3,400.3
XS GIS Cut Line= 3
1688419.97703817426269.2855334141688792.36039745426528.669804363
1688951.58638556426608.282798417
#Sta/Elev= 30
       0  1031.7    53.8 1015.49    61.7 1011.12    73.3 1003.05      80 1000.71
   111.6  997.35   146.1  995.79   197.8  996.18   271.6  995.11   281.1   992.3
   292.6  990.72     307  991.11   310.4992.3096   318.5  995.59   327.1  995.82
   338.6  998.11   365.8  998.66   370.2  999.64   380.4 1009.18   390.1 1025.17
     395 1029.77   414.5 1044.41   424.8 1050.69   433.4 1054.68   480.4 1068.62
   516.1 1083.84   556.4 1098.58   592.2 1106.38   611.5 1112.27   631.8 1116.79
#Mann= 6 ,-1,0
       0      .1       0     120     .05       0     240     .06       0
   281.1    .045       0   310.4     .06       0     390      .1       0
Bank Sta=281.1,310.4
XS Rating Curve= 0 ,0
Exp/Cntr(USF)=0,0
Exp/Cntr=0.3,0.1

Type RM Length L Ch R = 1 ,15240   ,505.4,505.4,505.4
XS GIS Cut Line= 2
1688183.15295277426662.3146180731688798.89525775426918.180508317
#Sta/Elev= 30
       0 1101.16    22.7 1095.93    39.2 1088.04    48.7 1081.22      66 1065.52
    83.3 1055.85   109.3 1029.38   139.7 1007.82     157  997.95   170.7  994.49
     183  993.09   252.3  995.34   259.5  994.13   265.6  991.23   280.9  989.44
   305.4  991.13   311.5  993.69   325.9  995.66   354.3  996.89   363.5 1001.92
   375.8 1004.62   395.2 1011.48   449.8 1024.82   468.9 1031.17   525.2 1057.41
   568.5 1075.22   599.1 1094.26   620.2 1101.44   651.2 1109.86   666.8 1116.83
#Mann= 5 ,-1,0
       0      .1       0   265.6    .045       0   305.4      .1       0
     320     .06       0     470      .1       0
Bank Sta=265.6,305.4
XS Rating Curve= 0 ,0
Exp/Cntr(USF)=0,0
Exp/Cntr=0.3,0.1

Type RM Length L Ch R = 1 ,14735   ,322.1,322.1,322.1
XS GIS Cut Line= 4
1688056.29372093427067.3706935541688116.61982513427169.301007554
1688424.49097762427289.9532159611688634.59223709 427400.20437192
#Sta/Elev= 30
       0  1051.6    38.9 1040.75    80.4 1026.82      99 1019.46   118.4 1009.44
   145.2 1002.62   160.9 1000.36   173.8  996.49   182.3  990.17   186.6  988.86
   195.2  988.78   212.4  989.01   215.7990.1284     221  992.78   228.6  993.73
   359.1  992.94   375.7  997.29   397.2  997.96     410 1000.53   418.6 1005.01
   447.7 1015.87   474.4 1030.86   498.4 1042.07   527.6 1058.88     539 1063.88
   552.6 1068.15   602.3 1097.95     652 1117.46   675.9 1134.22   686.4 1139.31
#Mann= 6 ,-1,0
       0      .1       0  148.44     .05       0   182.3    .045       0
   215.7     .05       0  238.44     .06       0  448.44      .1       0
Bank Sta=182.3,215.7
XS Rating Curve= 0 ,0
Exp/Cntr(USF)=0,0
Exp/Cntr=0.3,0.1

Type RM Length L Ch R = 1 ,14413   ,58.4,58.4,58.4
XS GIS Cut Line= 2
 1687912.3045449 427289.387406291688530.71335825427671.207999376
#Sta/Elev= 30
       0 1017.16    28.8 1016.82    97.4 1009.25   107.9 1007.36   135.8  999.31
   156.2  996.61     216  993.52   352.4  992.69   375.9  991.58   385.3  988.92
   394.5  987.47     412  987.62   418.2  988.95   429.4  995.69   438.1  996.86
   451.1  997.05   455.6  999.57   465.2 1011.09   469.9 1018.77   474.6 1025.15
     484 1034.83   487.5 1039.37   507.5 1059.84   521.6 1068.56   539.8 1081.76
   554.2 1090.61   568.6  1096.9   583.4  1100.1   615.4 1102.22   726.8    1100
#Mann= 7 ,-1,0
       0     .05       0     140     .06       0     170     .05       0
     370     .06       0   385.3    .045       0   418.2     .06       0
     540      .1       0
Bank Sta=385.3,418.2
XS Rating Curve= 0 ,0
Exp/Cntr(USF)=0,0
Exp/Cntr=0.3,0.1

Type RM Length L Ch R = 1 ,14355   ,420,420,420
XS GIS Cut Line= 2
1687880.68136695427350.2913045741688506.11755317427714.543465463
#Sta/Elev= 30
       0 1014.46    17.9 1010.52    52.2  998.95      68  996.18     129  994.47
   156.7  994.76   208.9  992.47   311.3  992.27   355.2  993.11   360.4  992.13
   366.9  989.47   372.7  988.67   390.3  987.46   404.9  987.64   409.8  988.69
   420.6  996.46   448.8  998.32   462.2 1011.29   472.2 1024.15   475.1 1027.45
   480.8 1031.91     490 1043.31   507.3 1060.27   522.4 1069.48   545.3 1078.26
   577.5    1083   640.3  1087.5   656.7 1086.04   675.2 1083.26   723.8 1080.66
#Mann= 6 ,-1,0
       0     .05       0      50      .1       0      60     .05       0
   372.7    .045       0   409.8     .06       0     510      .1       0
#XS Ineff= 2 , 0
          149.31 1002.34
Permanent Ineff=
       F       F
Bank Sta=372.7,409.8
XS Rating Curve= 0 ,0
Exp/Cntr(USF)=0,0
Exp/Cntr=0.3,0.1

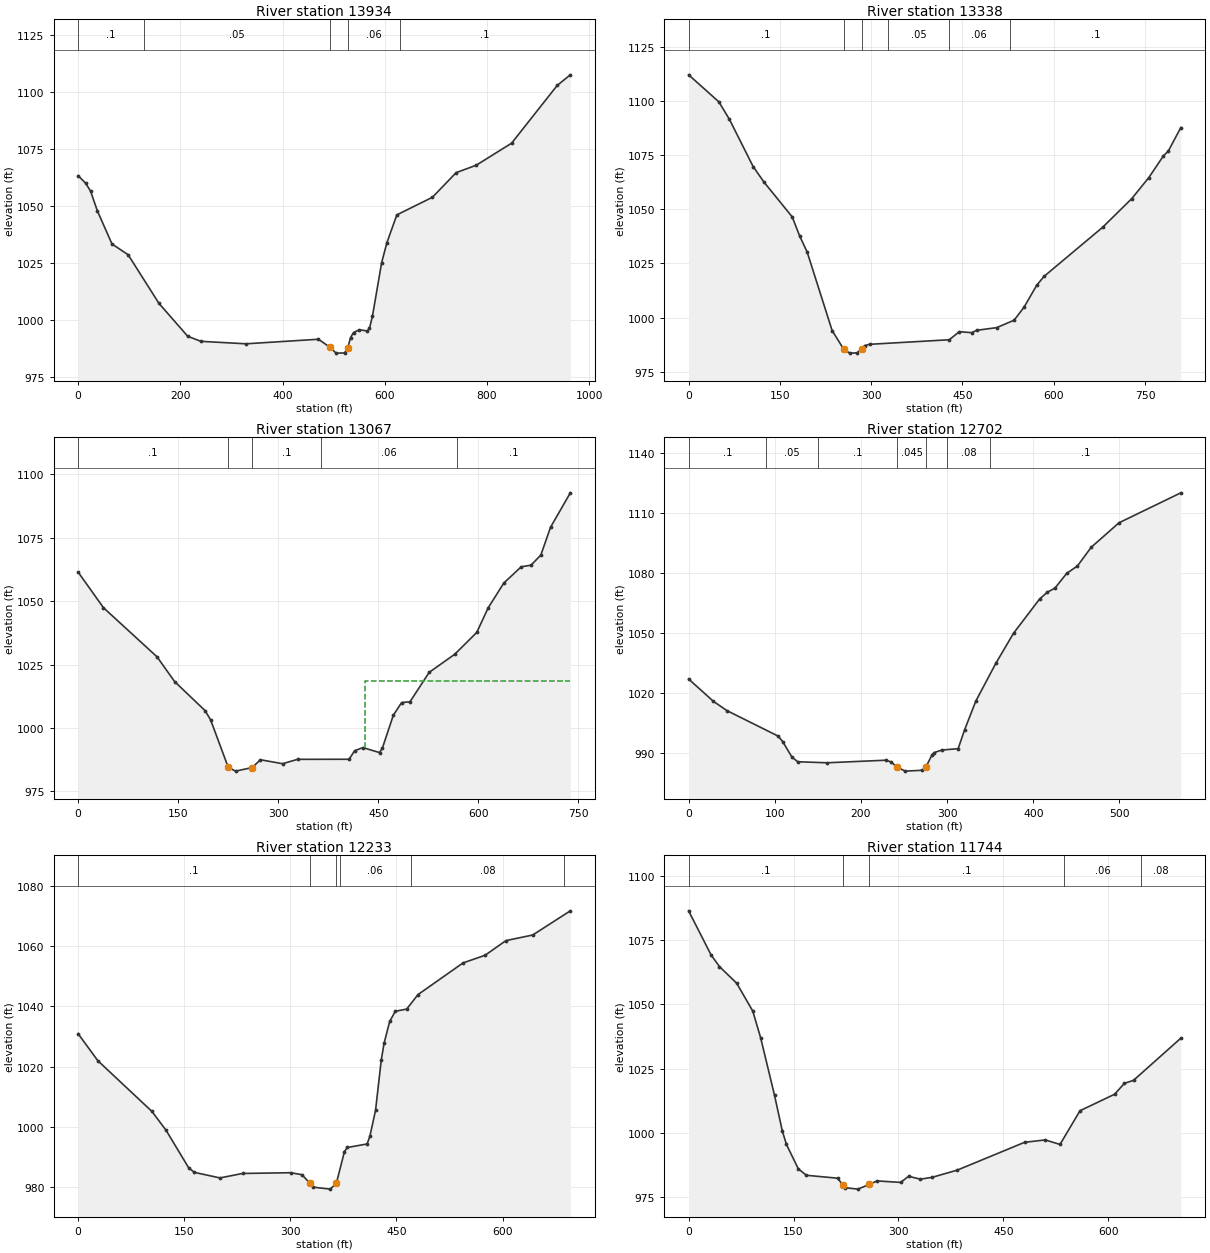
Type RM Length L Ch R = 1 ,13934   ,596.5,596.5,596.5
XS GIS Cut Line= 4
1687541.97951178427512.3131644071687618.25389641427590.898894021
1688073.58885917427956.0914022281688297.78932307 428106.32882649
#Sta/Elev= 30
       0 1063.24    14.6 1059.96    24.3 1056.47    37.5 1047.86    66.2 1033.27
    97.8 1028.55     158 1007.24   214.4  992.78   240.1  990.56   328.3  989.47
   470.2  991.47   493.3  987.86   504.7  985.38   521.3  985.45   527.7  987.83
   533.1  992.23   538.8   994.4   550.2  995.62   566.1  995.11   570.1   996.3
   575.8 1001.48   593.9 1025.12   604.1 1033.79   623.6 1046.04   693.2 1053.76
   739.6 1064.56     779 1067.83   848.2  1077.5   937.5 1102.86   963.1 1107.49
#Mann= 5 ,-1,0
       0      .1       0  129.51     .05       0   493.3    .045       0
   527.7     .06       0  629.51      .1       0
Bank Sta=493.3,527.7
XS Rating Curve= 0 ,0
Exp/Cntr(USF)=0,0
Exp/Cntr=0.3,0.1

Type RM Length L Ch R = 1 ,13338   ,270.6,270.6,270.6
XS GIS Cut Line= 4
1687322.17911693428213.0156519761687467.79385121428273.341756179
1687881.75573868 428364.871017731688108.49868207428377.352280669
#Sta/Elev= 30
       0 1111.94    49.7 1099.48      67 1091.44     106 1069.66   123.6 1062.56
   170.2 1046.45   182.5 1037.61   194.8 1030.23   235.8  994.04   254.5  985.58
   264.6  983.63   276.7  983.75   284.4985.6756     289  987.06   297.2  987.69
   428.3   989.8   444.7  993.51   465.2  993.07   473.4  994.16   506.1  995.38
   534.8  998.81   551.2 1004.83   571.7 1014.81   583.9 1018.99   680.1 1041.61
   728.2 1054.89   756.2 1064.59   780.2  1074.6   788.2  1076.8   808.7 1087.64
#Mann= 6 ,-1,0
       0      .1       0   254.5    .045       0   284.4      .1       0
  327.62     .05       0  427.62     .06       0  527.62      .1       0
Bank Sta=254.5,284.4
XS Rating Curve= 0 ,0
Exp/Cntr(USF)=0,0
Exp/Cntr=0.3,0.1

Type RM Length L Ch R = 1 ,13067   ,364.9,364.9,364.9
XS GIS Cut Line= 4
1687309.85479717428439.9783158121687420.10595312428533.587787852
1687779.98236786428633.4378913621687971.36173292428741.608836831
#Sta/Elev= 30
       0 1061.49    37.9 1047.48   118.3 1028.08   144.6 1018.34   190.3 1006.87
   198.6 1003.22     225  984.51     236  983.01   260.9  984.42   273.3  987.49
   306.5  985.94     329  987.66   406.2  987.69   414.5  991.04   426.9  992.29
   451.8  990.33     456  992.01   472.6 1005.11     485 1010.05   497.5 1010.37
   526.3 1021.97   564.5 1029.08   597.6 1037.71   614.7  1047.4   638.2  1057.2
   664.3 1063.61   678.9 1064.22   693.7 1068.24   708.3 1079.23   737.9 1092.77
#Mann= 5 ,-1,0
       0      .1       0     225    .045       0   260.9      .1       0
  364.63     .06       0   568.1      .1       0
#XS Ineff= 2 , 0
                          429.62          1018.7
Permanent Ineff=
       F       F
Bank Sta=225,260.9
XS Rating Curve= 0 ,0
Exp/Cntr(USF)=0,0
Exp/Cntr=0.3,0.1

Type RM Length L Ch R = 1 ,12702   ,469.7,469.7,469.7
XS GIS Cut Line= 3
1687234.87876065428691.0303307521687500.68343435428989.193834289
1687657.85489357429058.534183948
#Sta/Elev= 30
       0  1027.2    28.8 1016.04    44.4 1011.43   103.9  998.68   109.2  995.92
   119.9   988.2   126.6  985.86   160.6  985.35   228.6  986.63   234.3  985.89
     242983.2282   251.3  981.18   271.1  981.61   275.3  983.17   282.4  989.24
   285.3  990.48   293.7  991.71   312.8   992.4   320.4 1001.96   333.4 1016.26
   356.5 1035.01   377.1 1050.08   407.4  1067.2   416.3 1070.56   425.1 1072.58
   438.7 1079.93   451.3  1083.7   467.2    1093   499.4 1105.23   571.2 1120.21
#Mann= 7 ,-1,0
       0      .1       0      90     .05       0     150      .1       0
     242    .045       0   275.3      .1       0     300     .08       0
     350      .1       0
Bank Sta=242,275.3
XS Rating Curve= 0 ,0
Exp/Cntr(USF)=0,0
Exp/Cntr=0.3,0.1

Type RM Length L Ch R = 1 ,12233   ,488.9,488.9,488.9
XS GIS Cut Line= 3
  1686980.055287428684.1378999961686991.85008047429181.204196531
1687145.18239568429307.576983785
#Sta/Elev= 30
       0 1030.91    27.8 1021.96   104.4  1005.1   124.4  998.82   156.4  986.35
   164.4  984.88   200.5  983.04   232.5  984.52   300.5  984.77   316.5   984.1
   327.5  981.31   332.5  979.97   356.5  979.32   365.1  981.28   376.5  991.77
   380.5  993.14   408.5  994.31   412.5  996.88   420.5 1005.51   428.5 1022.03
   432.5  1027.7   440.5 1035.02   448.5 1038.37   464.5 1039.09   480.5  1043.9
   544.2 1054.42   575.3 1056.95   604.9 1061.83   642.7 1063.68   695.9 1071.71
#Mann= 6 ,-1,0
       0      .1       0   327.5    .045       0   365.1      .1       0
     370     .06       0     470     .08       0  687.21      .1       0
Bank Sta=327.5,365.1
XS Rating Curve= 0 ,0
Exp/Cntr(USF)=0,0
Exp/Cntr=0.3,0.1

Type RM Length L Ch R = 1 ,11744   ,510.2,510.2,510.2
XS GIS Cut Line= 4
1686419.56414308428879.8851934531686419.56414308428967.878097171
1686707.88131696429258.0674604961686904.46120825429321.721901484
#Sta/Elev= 30
       0 1086.32    32.1 1069.17    44.1 1064.65    68.7 1058.17    91.7 1047.35
     103 1036.93   122.8 1014.61     134 1000.65   139.9  995.46   156.7  986.06
   168.2  983.49     213  982.35   220.1 979.832   224.2  978.66     242   978.1
   258.6  979.95   269.4   981.3   303.2  980.71   314.5   983.1   331.4  981.97
   348.3   982.7   383.9  985.47   480.4  996.31   509.9  997.23     531  995.48
   559.6 1008.59     609 1014.99   623.1 1019.24   636.1  1020.4   703.7 1036.79
#Mann= 5 ,-1,0
       0      .1       0   220.1    .045       0   258.6      .1       0
  537.06     .06       0  647.06     .08       0
Bank Sta=220.1,258.6
XS Rating Curve= 0 ,0
Exp/Cntr(USF)=0,0
Exp/Cntr=0.3,0.1

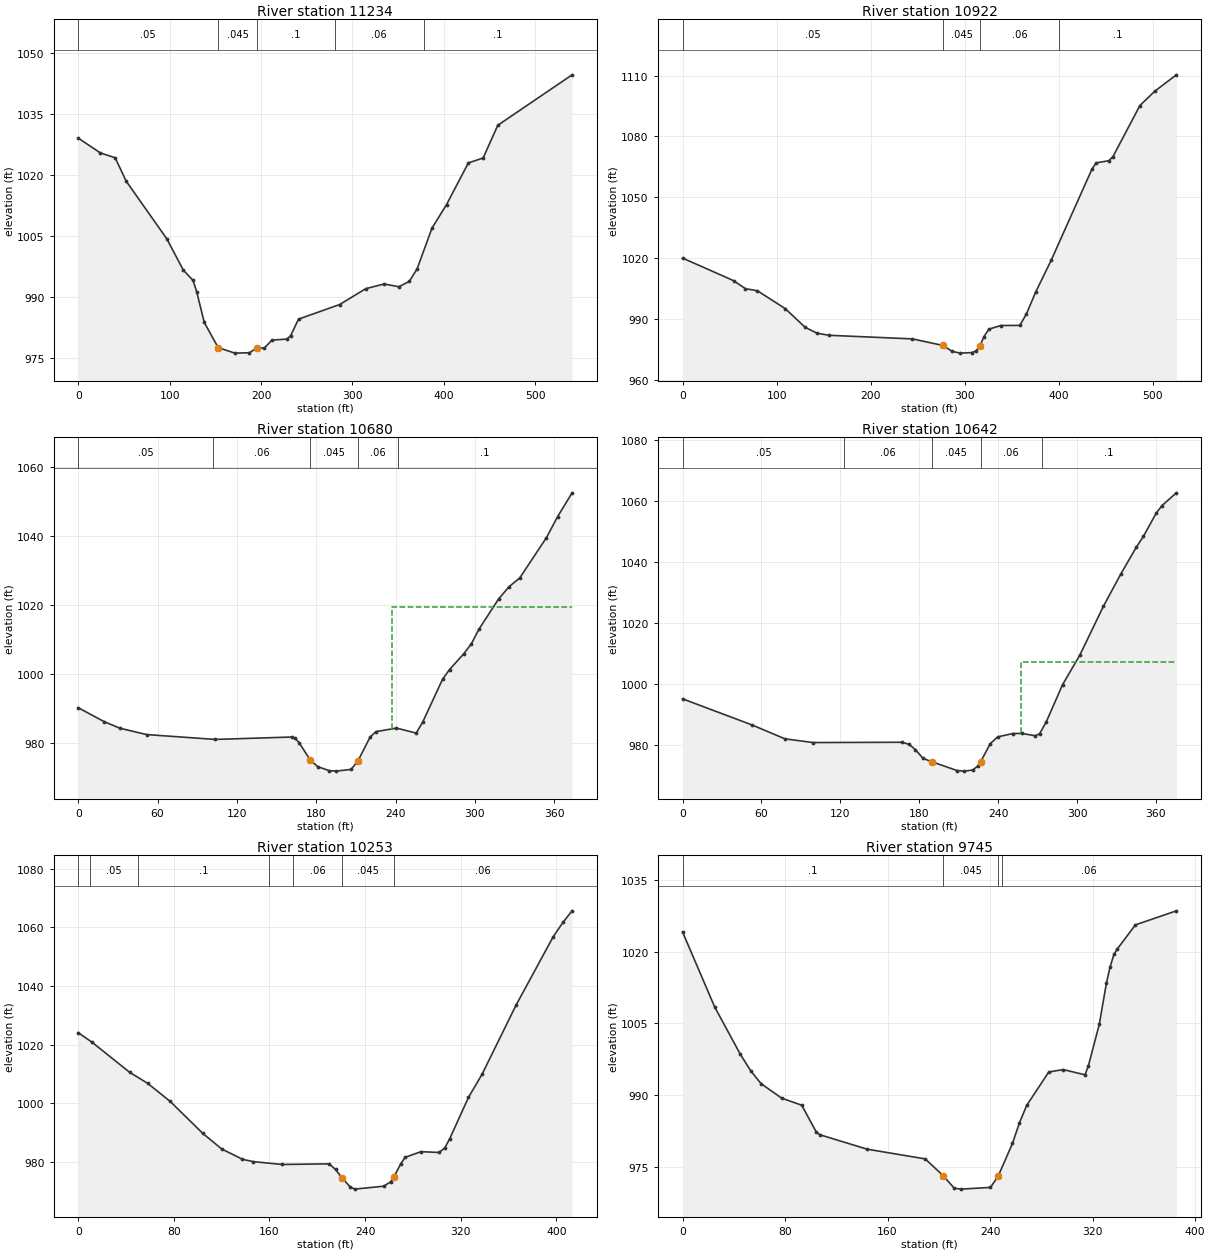
Type RM Length L Ch R = 1 ,11234   ,312.1,312.1,312.1
XS GIS Cut Line= 4
1686380.13137495429515.3844772881686489.45394575429531.352942685
1686681.34880307429485.0700023421686913.18314404429468.125420157
#Sta/Elev= 30
       0 1028.99    24.2 1025.36    40.4 1024.16    52.5  1018.4      97 1004.21
     115  996.54   125.6  994.03   129.7  991.15   137.9  983.69   153.1977.5162
   171.4  976.16   187.3  976.26   195.5  977.43   203.7  977.44     212  979.36
   228.4  979.61   232.5  980.49     241  984.51     286   988.1   314.6     992
   334.7  993.15   350.8  992.47   362.2  993.78   370.8  996.88   386.9 1006.82
   402.9 1012.64   426.8 1022.89     443 1024.11     459 1032.14   540.3 1044.54
#Mann= 5 ,-1,0
       0     .05       0   153.1    .045       0   195.5      .1       0
  280.48     .06       0  377.88      .1       0
Bank Sta=153.1,195.5
XS Rating Curve= 0 ,0
Exp/Cntr(USF)=0,0
Exp/Cntr=0.3,0.1

Type RM Length L Ch R = 1 ,10922   ,241.8,241.8,241.8
XS GIS Cut Line= 3
 1686372.8254944429702.2123746521686768.06548746429837.426056488
1686865.15083663429883.109125862
#Sta/Elev= 30
       0 1019.97    54.2 1008.84    66.9 1004.87    79.6 1003.84   109.2  995.02
   130.4  985.79     143  982.91   155.7  981.88   244.4   980.1     277976.8428
   286.7  973.94   295.2  973.08   307.9  973.36   312.1  974.25   316.3  976.81
   316.3  976.84   320.5  981.27   325.7   984.9   338.3   986.7   358.6  986.75
   365.6  992.44   375.5 1003.27   391.9 1018.87   435.5 1064.09   439.9 1066.93
   453.1 1067.97   457.6 1070.04   486.2 1095.18   501.8 1102.19     525 1110.34
#Mann= 4 ,-1,0
       0     .05       0     277    .045       0   316.3     .06       0
     400      .1       0
Bank Sta=277,316.3
XS Rating Curve= 0 ,0
Exp/Cntr(USF)=0,0
Exp/Cntr=0.3,0.1

Type RM Length L Ch R = 1 ,10680   ,37.4,37.4,37.4
XS GIS Cut Line= 3
1686457.01296716429837.0490508951686461.75644385429918.636850018
1686653.68538313430138.355103132
#Sta/Elev= 30
       0  990.22    19.5  986.19    31.5  984.27    51.7  982.42   103.6  981.01
   161.3  981.71   163.9  981.38     167  980.11   175.5     975   181.1  973.12
   189.6  971.97   194.8  971.81   206.4  972.31   211.7  974.89   220.8  981.73
   225.2  983.28   240.7   984.3   255.6  982.85   260.5  986.03   275.5  998.45
   280.8  1001.3   291.7 1005.92   297.4 1008.82     303 1012.97   317.9 1021.77
   325.7 1025.29   333.9 1027.88   354.1 1039.57   362.6 1045.71   373.5 1052.59
#Mann= 5 ,-1,0
       0     .05       0  101.73     .06       0   175.5    .045       0
   211.7     .06       0  241.73      .1       0
#XS Ineff= 2 , 0
                          236.95         1019.32
Permanent Ineff=
       F       F
Bank Sta=175.5,211.7
XS Rating Curve= 0 ,0
Exp/Cntr(USF)=0,0
Exp/Cntr=0.3,0.1

Type RM Length L Ch R = 1 ,10642   ,389.2,389.2,389.2
XS GIS Cut Line= 3
1686425.34808582429851.5777602761686421.35114318429924.584648958
1686615.73177116430156.287931563
#Sta/Elev= 30
       0  995.24      53  986.66    77.9  982.14    99.2  980.92     167  981.01
   172.3  980.32     177  978.64   182.9  975.75   189.4  974.66   208.8  971.75
     214  971.56   220.6  971.92   224.5  973.19   226.8  974.66     234  980.54
   239.7  982.77   251.1  983.87   257.9  983.91   268.1  983.16   271.5  983.77
   276.6  987.66     289  999.84   302.2 1009.59   320.1 1025.56   333.4 1036.17
     345 1044.81   350.5 1048.43   360.2 1056.01   364.6 1058.52   375.6 1062.71
#Mann= 5 ,-1,0
       0     .05       0  123.12     .06       0   189.4    .045       0
   226.8     .06       0  273.12      .1       0
#XS Ineff= 2 , 0
                          257.37         1007.22
Permanent Ineff=
       F       F
Bank Sta=189.4,226.8
XS Rating Curve= 0 ,0
Exp/Cntr(USF)=0,0
Exp/Cntr=0.3,0.1

Type RM Length L Ch R = 1 ,10253   ,508.6,508.6,508.6
XS GIS Cut Line= 2
1686053.88602514430098.1149075791686325.16627512430409.834449473
#Sta/Elev= 30
       0 1024.06    11.8 1020.72      43 1010.55    58.2 1006.75      77 1000.59
     104  989.79   119.9  984.44   137.4  980.87   146.4  980.08   170.6  979.11
     210  979.32   215.3   977.4   220.6   974.6   227.3  971.55   231.2   970.7
   255.6   971.7   261.3  973.17   264.1   974.8   269.8  979.34   273.6  981.56
   286.8  983.48     302   983.2   306.7  984.76   310.8  987.89   326.5 1001.97
   337.9 1009.89   366.2 1033.35   397.4 1056.78   405.5 1061.65   413.2 1065.61
#Mann= 7 ,-1,0
       0      .1       0      10     .05       0      50      .1       0
     160     .05       0     180     .06       0   220.6    .045       0
   264.1     .06       0
Bank Sta=220.6,264.1
XS Rating Curve= 0 ,0
Exp/Cntr(USF)=0,0
Exp/Cntr=0.3,0.1

Type RM Length L Ch R = 1 ,9745    ,502,502,502
XS GIS Cut Line= 3
1685659.16813923430514.6819376651685738.21613785430523.002779624
1685954.55802878430739.344670562
#Sta/Elev= 30
       0 1024.14    25.1 1008.44    45.2  998.51    53.2  995.11    61.3  992.41
    77.4  989.38      93  987.91   104.5  982.24   107.4  981.71   144.1  978.71
   189.4  976.68   203.5  973.15     212  970.56   217.4  970.36   240.3  970.72
   246.3973.0535   257.5  979.94   262.9  984.21   268.6  987.87   285.8  994.85
   297.1  995.36   314.1  994.26   316.7  996.13   325.2 1004.79   330.8 1013.43
   333.6 1016.77   336.7 1019.47   339.3 1020.58   353.4 1025.61   385.4 1028.55
#Mann= 4 ,-1,0
       0      .1       0   203.5    .045       0   246.3      .1       0
  249.48     .06       0
Bank Sta=203.5,246.3
XS Rating Curve= 0 ,0
Exp/Cntr(USF)=0,0
Exp/Cntr=0.3,0.1